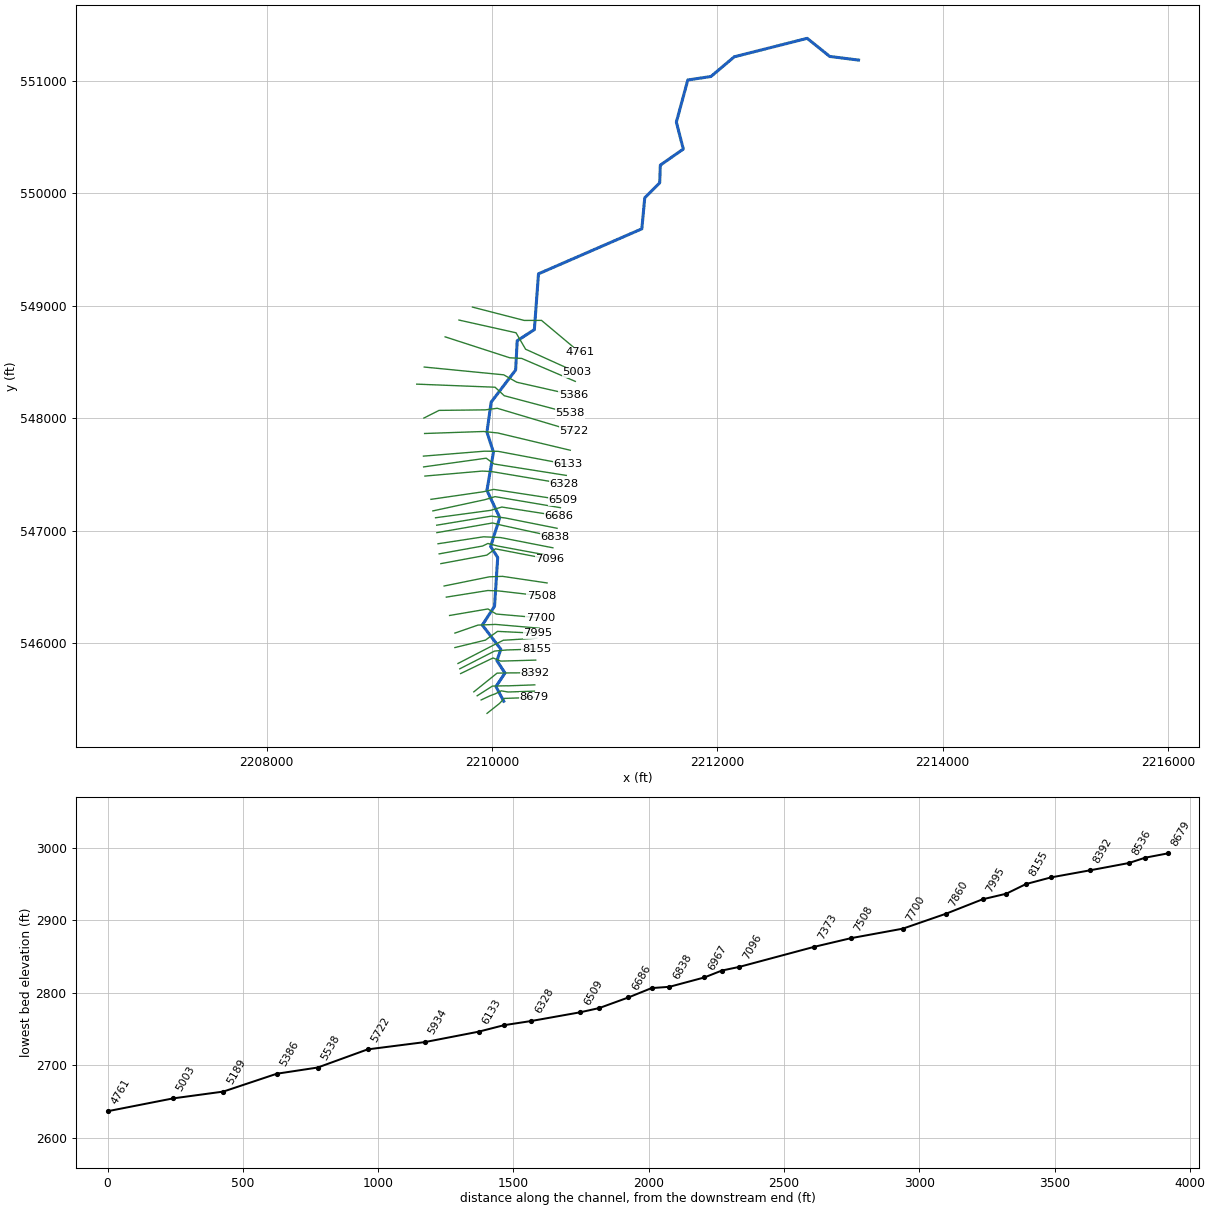
--- CHIMRCKRN.prj (project) ---

Proj Title=CHIMRCKRN
Current Plan=p01
Default Exp/Contr=0,0
English Units
Geom File=g01
Flow File=f01
Plan File=p01
Background Map Layer=Inundation Boundary (P100yr Value_0)
BEGIN DESCRIPTION:
----------MODEL BY WOOD PLC 2022----------
AFH study
Randolph County, WV
HEC-RAS Version: RAS 6.2
Vertical Datum: NAVD88
Projection: NAD 1983 StatePlane West Virginia S FIPS 4702 (US Feet)
Terrain: 1-meter LIDAR (FEMA Region III 3DEP collected 2016-2018)
Land Use: 2019 NLCD
Hydrologic Method:
WV SIR2010-5033 regression equations
Additional Model Notes:
None
END DESCRIPTION:
DSS File=dss
DSS Export Rating Curves= 0
DSS Export Rating Curve Sorted= 0
DSS Export Volume Flow Curves= 0
DXF OffsetX= 0
DXF OffsetY= 0
DXF ScaleX= 0
DXF ScaleY= 0

--- CHIMRCKRN.p01 (plan) ---

Plan Title=Floodplain
Program Version=6.20
Short Identifier=Floodplain
Geom File=g01
Flow File=f01
Subcritical Flow
K Sum by GR= 0
Std Step Tol= 0.01
Critical Tol= 0.01
Num of Std Step Trials= 20
Max Error Tol= 0.3
Flow Tol Ratio= 0.001
Split Flow NTrial= 30
Split Flow Tol= 0.02
Split Flow Ratio= 0.02
Log Output Level= 0
Friction Slope Method= 1
Unsteady Friction Slope Method= 2
Unsteady Bridges Friction Slope Method= 1
Parabolic Critical Depth
Global Vel Dist= 0 , 0 , 0
Global Log Level= 0
CheckData=True
Encroach Param=-1 ,0,0, 0
Computation Interval=0.1SEC
Output Interval=1SEC
Instantaneous Interval=Max Profile
Mapping Interval=1HOUR
Computation Time Step Use Courant=        0
Computation Time Step Use Time Series=    0
Computation Time Step Count To Double=0
Computation Time Step Max Doubling=0
Computation Time Step Max Halving=0
Computation Time Step Residence Courant=0
Run HTab= 0
Run UNet= 0
Run Sediment= 0
Run PostProcess= 0
Run WQNet= 0
Run RASMapper=-1
UNET Theta= 0
UNET Theta Warmup= 0
UNET ZTol= 0
UNET ZSATol= 0
UNET MxIter= 0
UNET Max Iter WO Improvement= 0
UNET MaxInSteps= 0
UNET DtIC= 0
UNET DtMin= 0
UNET MaxCRTS= 0
UNET WFStab= 0
UNET SFStab= 0
UNET WFX= 1
UNET SFX= 1
UNET Gravity=32.174
UNET 1D Methodology=Finite Difference
UNET DSS MLevel= 1
UNET Pardiso=0
UNET DZMax Abort= 0
UNET Use Existing IB Tables= 0
UNET Froude Reduction=False
UNET Froude Limit= 0
UNET Froude Power= 0
UNET D1 Cores= 0
UNET WindReference=Eulerian
UNET WindDragFormulation=Hsu (1988)
UNET D2 Coriolis=0
UNET D2 Cores= 0
UNET D2 Theta= 1
UNET D2 Theta Warmup= 1
UNET D2 Z Tol= 0.01
UNET D2 Volume Tol= 0.01
UNET D2 Max Iterations= 20
UNET D2 Equation= 0
UNET D2 RampUpFraction=0.1
UNET D2 TimeSlices= 1
UNET D2 Turbulence Formulation=Non-Conservative (original)
UNET D2 Eddy Viscosity=0.3
UNET D2 Transverse Eddy Viscosity=0.1
UNET D2 Smagorinsky Mixing=0
UNET D2 BCVolumeCheck=0
UNET D2 Cores=0
UNET D2 SolverType=PARDISO (Direct)
UNET D2 Minimum Iterations= 2147483647
UNET D2 Maximum Iterations= 2147483647
UNET D2 Restart Number= 10
UNET D2 Relaxation Coeff=1.3
UNET D2 SOR Precondition Iterations= 10
UNET D2 ILUT Maximum Fill= 8
UNET D2 ILUT Tolerance=1E-08
UNET D1D2 MaxIter= 0
UNET D1D2 ZTol=0.01
UNET D1D2 QTol=0.1
UNET D1D2 MinQTol=1
DSS File=dss
Write IC File= 0
Write IC File at Fixed DateTime=0
Write IC File at Sim End=0
Echo Input=False
Echo Parameters=False
Echo Output=False
Write Detailed= 0
HDF Write Warmup=0
HDF Write Time Slices=0
HDF Flush=0
HDF Compression= 1
HDF Chunk Size= 1
HDF Spatial Parts= 1
HDF Use Max Rows=0
HDF Fixed Rows= 1
Calibration Method= 0
Calibration Iterations= 20
Calibration Max Change=0.05
Calibration Tolerance=0.2
Calibration Maximum=1.5
Calibration Minimum=0.5
Calibration Optimization Method= 1
WQ AD Non Conservative
WQ ULTIMATE=-1
WQ Max Comp Step=1HOUR
WQ Output Interval=15MIN
WQ Output Selected Increments= 0
WQ Output face flow=0
WQ Output face velocity=0
WQ Output face area=0
WQ Output face dispersion=0
WQ Output cell volume=0
WQ Output cell surface area=0
WQ Output cell continuity=0
WQ Output cumulative cell continuity=0
WQ Output face conc=0
WQ Output face dconc_dx=0
WQ Output face courant=0
WQ Output face peclet=0
WQ Output face adv mass=0
WQ Output face disp mass=0
WQ Output cell mass=0
WQ Output cell source sink temp=0
WQ Output nsm pathways=0
WQ Output nsm derived pathways=0
WQ Create Restart=0
WQ Fixed Restart=0
WQ System Summary=0
WQ Write To DSS=0
Sorting and Armoring Iterations= 10
XS Update Threshold= 0.02
Bed Roughness Predictor= 0
Hydraulics Update Threshold= 0.02
Energy Slope Method= 1
Volume Change Method= 1
Sediment Retention Method= 0
Sediment TS Multiplier= 1
Warm Up Method= 0
XS Weighting Method= 0
Number of US Weighted Cross Sections= 1
Number of DS Weighted Cross Sections= 1
Upstream XS Weight=0
Main XS Weight=1
Downstream XS Weight=0
Number of DS XS's Weighted with US Boundary= 1
Upstream Boundary Weight= 1
Weight of XSs Associated with US Boundary= 0
Number of US XS's Weighted with DS Boundary= 1
Downstream Boundary Weight= 0.5
Weight of XSs Associated with DS Boundary= 0.5
Percentile Method= 0
Sediment Output Level= 3
Mass or Volume Output= 0
Output Increment Type= 1
Profile and TS Output Increment= 1
Transport Output Increment 1
XS Output Flag= 0
XS Output Increment= 10
Read HDF5 Sediment Hotstart= 0
Sediment Hotstart Type= 0
Write Gradation File= 0
Read Gradation Hotstart= 0
Write HDF5 File= 1
Write Binary Output= 1
Write DSS Sediment File= 0
DSS Sediment Output Type= 1
SV Curve= 0
Specific Gage Flag= 0
Subcell Erosion Methods= 0
Subcell Deposition Methods= 0
Advection Scheme= 1
Matrix Solver= 0
Implicit Weighting Factor= 1
Maximum Outer Loop Convergence Iterations= 5
Convergence Maximum Absolute= 0.001
Convergence RMSE= 0.0001
Grain Fractions Max Abs Error= 0.001
Max Subgrid Regions= 1
Max Subgrid Length Scale= 3.402823E+38
Initial Layer Thickness= 3.402823E+38
Min Layer Thickness= 3.402823E+38
Max Layer Thickness= 3.402823E+38
Number of Layers= 5

--- CHIMRCKRN.f01 (steady flow) ---

Flow Title=Flow
Program Version=6.20
Number of Profiles= 1
Profile Names=P100yr
River Rch & RM=CHIMRCKRN,Main,8679
     379
River Rch & RM=CHIMRCKRN,Main,5538
     422
River Rch & RM=CHIMRCKRN,Main,4423
     502
River Rch & RM=CHIMRCKRN,Main,1696
     564
Boundary for River Rch & Prof#=CHIMRCKRN,Main            , 1
Up Type= 0
Dn Type= 3
Dn Slope=0.08376
DSS Import GetInterval= 0
DSS Import GetPeak= 0
DSS Import FillOption= 0

--- CHIMRCKRN.g01 (geometry) ---

Geom Title=Geometry
Program Version=6.20

River Reach=CHIMRCKRN       ,Main
Reach XY= 30
     2210104.236      545486.003     2210035.254         545616.
     2210115.174      545736.524     2210043.437      545846.027
     2210078.598      545947.288     2209914.132      546162.566
     2210022.465      546330.274      2210050.59      546762.869
     2209987.669      546861.071     2210068.646      547117.579
     2209954.983       547359.78     2210012.743      547698.677
     2209955.104      547878.538     2209992.257      548143.816
     2210209.653      548429.753     2210223.693       548689.67
     2210375.892       548788.91     2210412.643      549284.647
     2211329.792      549684.383     2211355.746      549960.598
     2211488.299       550092.89     2211494.028      550250.702
     2211697.934      550393.411     2211636.215       550632.82
      2211737.71       551007.382211943.21846629551038.377840273
2212150.23107331551213.511618538     2212797.596      551377.552
     2212997.454      551216.586     2213253.345      551184.227

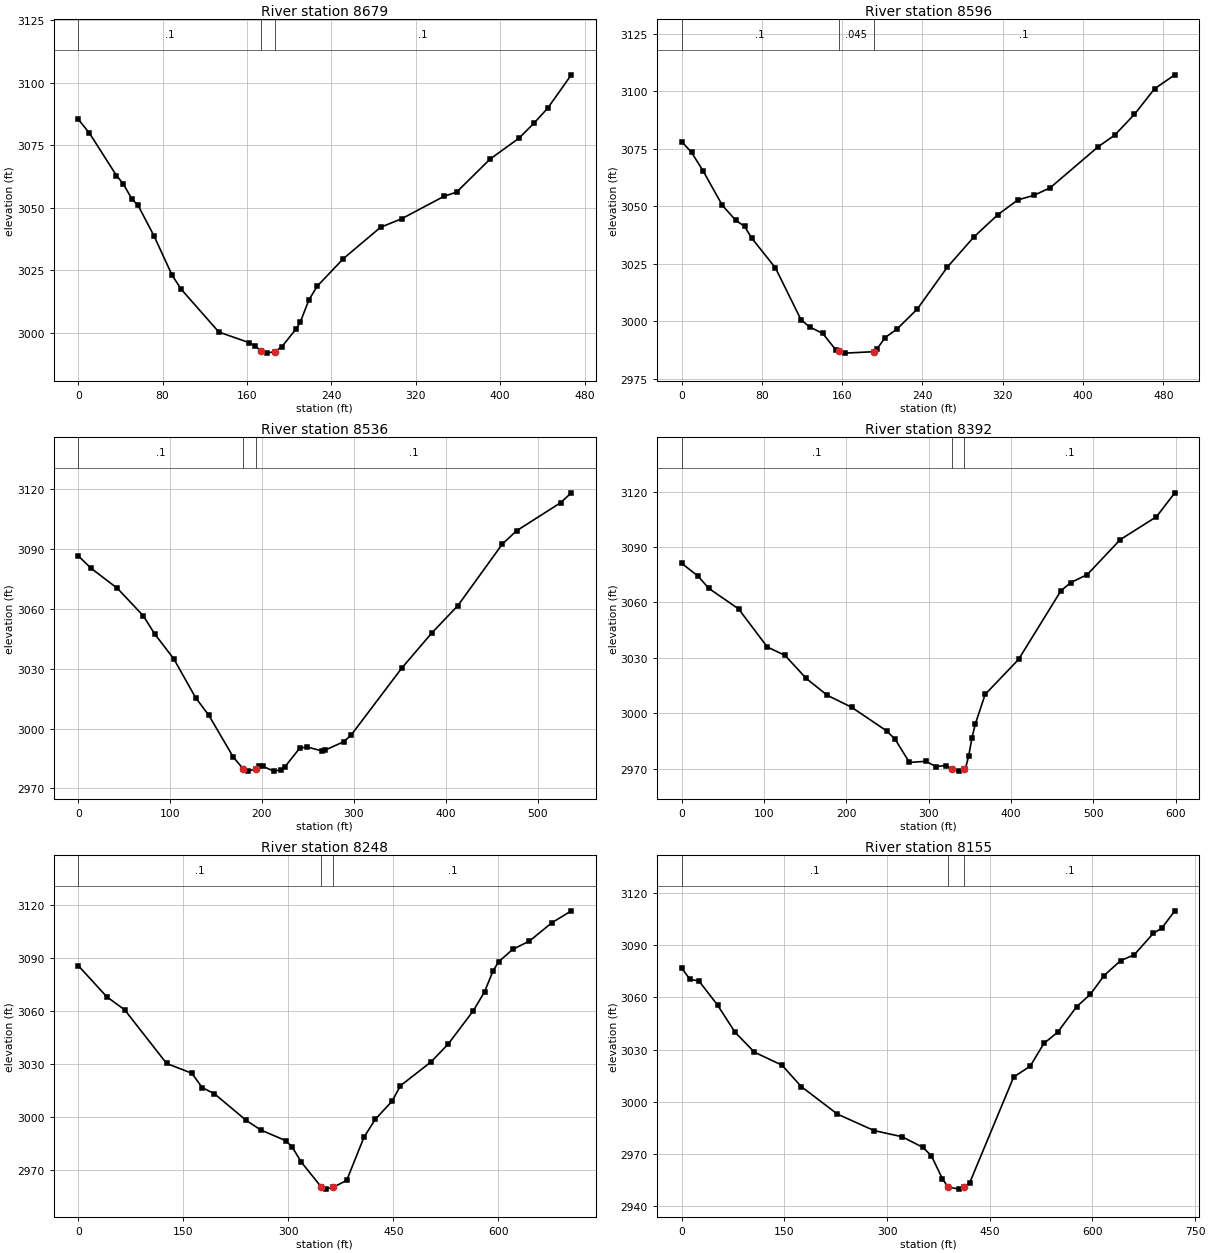
Type RM Length L Ch R = 1 ,8679    ,83.6,83,81.4
XS GIS Cut Line= 4
 2209955.7920468545377.7756165842210065.72022021545465.142202654
2210108.73017091 545510.748518122210372.87472056545519.659803254
#Sta/Elev= 30
       0 3085.42    10.7 3079.81    36.3 3062.89    42.6 3059.65    51.1 3053.39
    56.8 3050.94      72 3038.67      89 3023.09    97.6 3017.47   133.3 3000.37
     162 2996.12     168 2994.87   173.1 2992.65     179 2991.94  186.562992.589
   193.1 2994.55   206.6 3001.64   210.6 3004.43   218.6 3013.15   226.6 3018.72
   251.4 3029.72   286.6 3042.23   306.6 3045.63   346.6 3054.58   358.6 3056.27
   390.5 3069.51   417.9 3077.87     432 3083.83     445 3089.82   467.4 3103.15
#Mann= 3 ,-1,0
       0      .1       0   173.1    .045       0  186.56      .1       0
Bank Sta=173.1,186.56
XS Rating Curve= 0 ,0
Exp/Cntr=0.3,0.1

Type RM Length L Ch R = 1 ,8596    ,65.3,60.4,62.3
XS GIS Cut Line= 6
2209903.54700761545497.0170330862209985.26677463545535.546208939
 2210026.4316556545550.3560053242210082.00168943545577.972581402
2210141.96281047545567.7005495862210376.37050558545575.468945312
#Sta/Elev= 30
       0 3078.04     9.8 3073.34    21.6 3065.08    40.5 3050.31    53.8 3043.83
    62.6 3041.17    69.7 3036.12    93.4 3023.12   118.9 3000.58   127.4 2997.46
   140.6 2994.59     154 2987.22  156.382986.774   162.9 2986.04   191.2 2986.66
   194.4 2987.69   202.7 2992.78   214.6 2996.52   234.9 3005.26   264.6 3023.35
   291.2 3036.55   315.2 3046.29   335.2  3052.7   351.2 3054.69   367.3 3057.96
   415.3 3075.86   431.5 3080.81   451.3 3089.91   471.3 3101.02   491.5 3107.07
#Mann= 3 ,-1,0
       0      .1       0  156.38    .045       0   191.2      .1       0
Bank Sta=156.38,191.2
XS Rating Curve= 0 ,0
Exp/Cntr=0.3,0.1

Type RM Length L Ch R = 1 ,8536    ,146.9,144,147.9
XS GIS Cut Line= 6
2209868.42143042545534.1566676072209963.42063684545594.798554434
2210003.47625393545620.4062885262210126.36342761545623.005164605
2210144.30539025 545622.620208072210379.86629059545631.278087369
#Sta/Elev= 30
       0 3086.68    13.9 3080.46    42.6 3070.38    70.9 3056.56    83.1 3047.58
   104.1 3034.96   127.8 3015.51   142.1 3006.75   168.9 2985.66  179.76 2979.72
     185  2978.7   193.62979.836     197 2981.06     201 2981.06     213 2978.68
     221  2979.4     225  2980.8     241 2990.14     249 2990.82     265 2988.84
     269 2989.26     289 2993.42     297 2996.69   352.3  3030.4     385 3048.01
   413.1 3061.58   461.7 3092.56   477.2 3099.21   525.1 3113.27   536.8 3118.25
#Mann= 3 ,-1,0
       0      .1       0  179.76    .045       0   193.6      .1       0
Bank Sta=179.76,193.6
XS Rating Curve= 0 ,0
Exp/Cntr(USF)=0,0
Exp/Cntr=0.3,0.1

Type RM Length L Ch R = 1 ,8392    ,148.8,143.7,141.3
XS GIS Cut Line= 4
2209838.35902292545568.9696158842210045.25959057545735.494333124
2210148.24447077545737.3594311482210378.40988645545738.854949997
#Sta/Elev= 30
       0 3081.11    19.5 3074.32    33.1 3067.51    69.1 3056.43   103.9 3035.84
   125.6 3031.22   151.2 3018.79   176.9 3009.64   206.3  3003.2   248.8  2990.4
   259.1  2985.9   276.5 2973.32   296.5 2973.91   308.5  2971.1   320.5 2971.63
     328 2969.54   336.5  2968.6   343.12969.528   344.5 2969.93   348.5 2976.86
   352.5 2986.73   356.5 2994.09   368.5 3010.17     409 3029.06   460.5 3066.27
   472.5  3070.7   492.5 3075.03   532.5 3093.94   576.5 3106.36   598.8  3119.3
#Mann= 3 ,-1,0
       0      .1       0     328    .045       0   343.1      .1       0
Bank Sta=328,343.1
XS Rating Curve= 0 ,0
Exp/Cntr(USF)=0,0
Exp/Cntr=0.3,0.1

Type RM Length L Ch R = 1 ,8248    ,84.8,92.5,96.7
XS GIS Cut Line= 4
2209721.34604353545731.4532987092210008.81421957545870.301987558
2210077.90856926545842.3661892282210387.99862373545851.218891684
#Sta/Elev= 30
       0 3085.71    40.8    3068    66.3  3060.6   126.2 3030.18   162.2 3024.63
   177.1 3016.42   194.2 3013.07     240 2997.83   260.8  2992.4   296.3 2986.38
   305.2 2982.94   318.5 2974.21   347.3 2959.96   353.1 2958.88  364.172959.987
   383.3 2963.83     408 2988.34   424.1 2998.49   448.1 3008.76   460.1 3017.55
   504.1 3031.17   528.1 3041.14   564.1 3060.08   580.1 3070.78   592.1 3082.56
   600.1  3087.8   620.1 3094.84   644.1 3099.57   676.2 3109.98     704 3116.75
#Mann= 3 ,-1,0
       0      .1       0   347.3    .045       0  364.17      .1       0
Bank Sta=347.3,364.17
XS Rating Curve= 0 ,0
Exp/Cntr=0.3,0.1

Type RM Length L Ch R = 1 ,8155    ,69.1,73,76.1
XS GIS Cut Line= 4
2209713.61097502 545773.702973252210022.52805958545931.666549428
2210131.63036704545941.3095280632210395.41274858545949.938399961
#Sta/Elev= 30
       0 3076.89    11.9  3070.5    25.3 3069.41    52.3 3055.65    77.9    3040
   106.2  3028.5   146.6 3021.01   174.6 3008.74   227.4 2992.89   280.9 2983.41
   321.9 2979.85   352.6 2973.68   364.7 2968.91   380.7  2955.8   388.8    2951
   404.8  2949.7   412.9 2950.85   420.9 2953.51     485 3014.24   509.1 3020.45
   529.1 3033.56   549.1 3039.93     577 3054.71   597.1 3061.84   617.1 3072.63
   641.1 3081.16   661.1 3084.56   689.2 3096.97   701.2 3099.81   720.4 3109.85
#Mann= 3 ,-1,0
       0      .1       0   388.8    .045       0   412.9      .1       0
Bank Sta=388.8,412.9
XS Rating Curve= 0 ,0
Exp/Cntr(USF)=0,0
Exp/Cntr=0.3,0.1

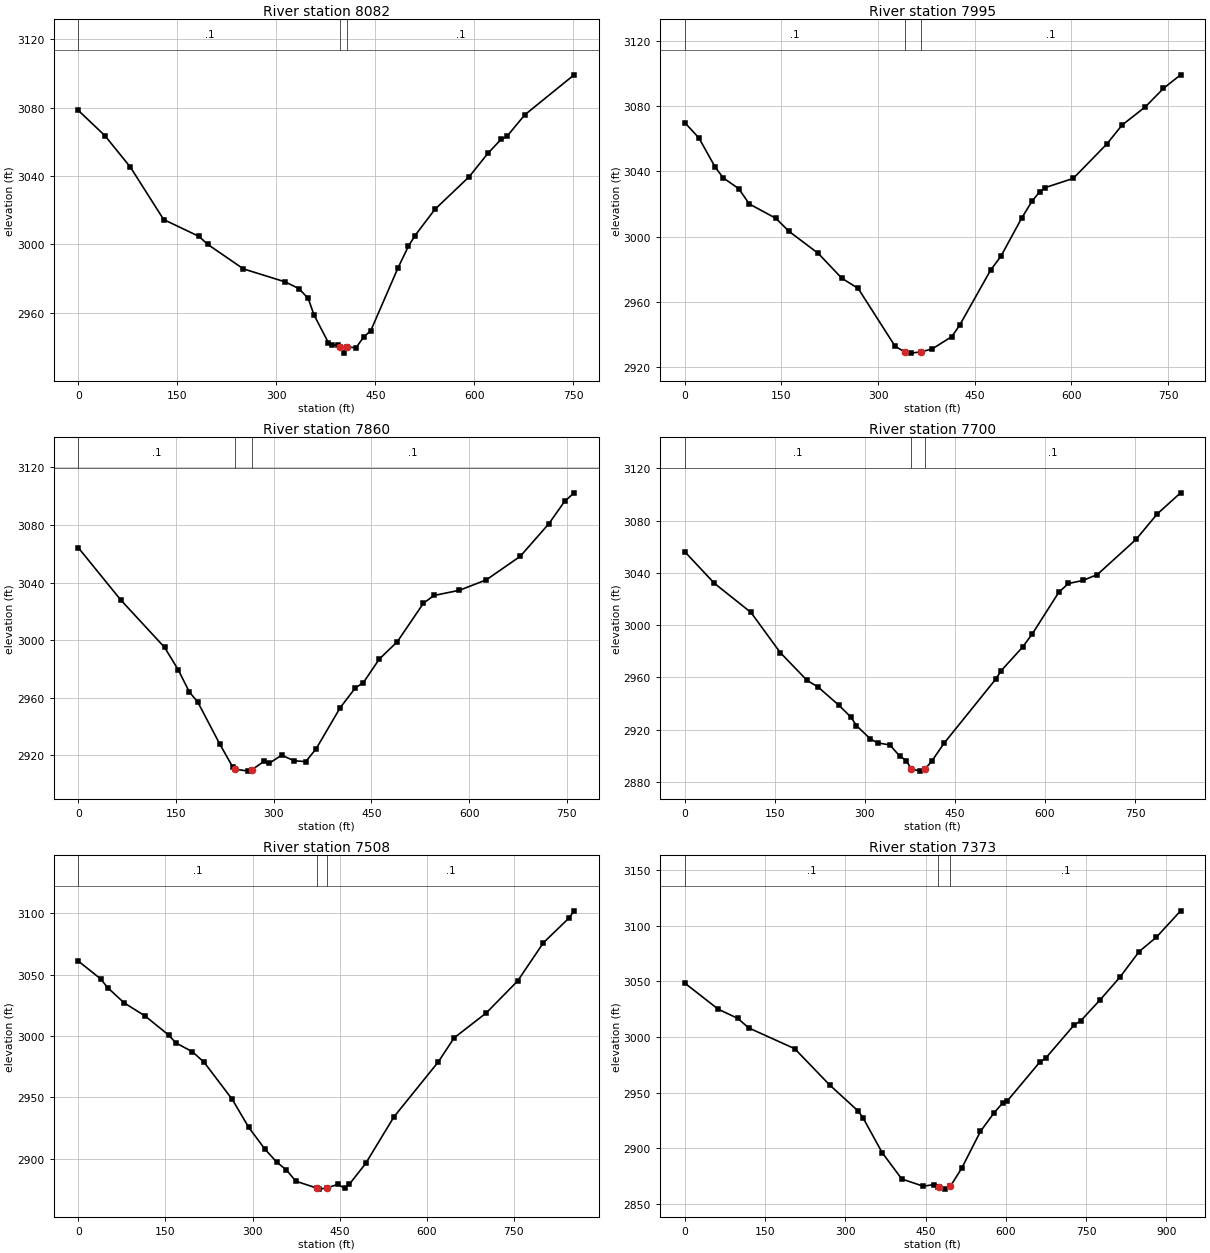
Type RM Length L Ch R = 1 ,8082    ,86.9,87.3,88.1
XS GIS Cut Line= 4
2209697.88334389545821.1770097612210013.70189101 545984.46955401
 2210100.5662201546027.7185223022210398.87287497546045.937176432
#Sta/Elev= 30
       0 3078.45    40.3 3063.67    78.9 3045.26   129.3 3014.58   182.8 3004.73
   196.2 3000.01   250.2 2985.69   313.4 2978.09   334.2 2974.16   348.4 2968.41
   357.1 2958.78   378.8  2942.6   384.8 2940.93   393.7 2941.29  396.892939.937
   402.7 2936.38   407.5 2939.94   420.9 2939.56   432.5 2945.83   443.2 2949.53
   484.2 2986.08   500.3 2999.02   510.3 3005.22   540.3 3020.52   592.4 3039.69
   620.5 3053.26   640.5 3061.47     650 3063.49   676.6 3075.89   751.4  3099.3
#Mann= 3 ,-1,0
       0      .1       0  396.89    .045       0   407.5      .1       0
Bank Sta=396.89,407.5
XS Rating Curve= 0 ,0
Exp/Cntr(USF)=0,0
Exp/Cntr=0.3,0.1

Type RM Length L Ch R = 1 ,7995    ,140,134.7,125.3
XS GIS Cut Line= 4
2209670.87440148545962.7432865162209941.96402806546029.042379973
2210048.82464982546106.681034808 2210406.7733921546089.127037225
#Sta/Elev= 30
       0 3069.89    21.9 3060.51    46.6 3043.02    59.3 3036.18    83.7 3029.42
   100.2 3020.05   141.3 3011.31   161.9 3003.25   207.2 2989.78   243.7 2974.57
     269 2968.37   326.3 2932.96   341.1 2929.49     351 2928.71   366.7 2929.49
   383.9 2931.27   414.5 2938.87   426.5 2945.77   474.6 2979.55   490.6 2988.05
   522.6 3011.25   538.7 3021.69   550.7 3027.52   558.7 3030.02   602.9 3035.74
   654.8 3056.74   678.8 3068.45   714.9 3079.61   742.9 3090.89   769.5 3099.18
#Mann= 3 ,-1,0
       0      .1       0   341.1    .045       0   366.7      .1       0
Bank Sta=341.1,366.7
XS Rating Curve= 0 ,0
Exp/Cntr(USF)=0,0
Exp/Cntr=0.3,0.1

Type RM Length L Ch R = 1 ,7860    ,166.6,160.1,151.3
XS GIS Cut Line= 4
2209671.04894099546091.4345067942209875.35748043546162.420739793
2210030.41918338546168.5164444192210418.68425976546135.033868526
#Sta/Elev= 30
       0 3064.17    65.1 3027.89   132.5 2994.87   153.1 2979.52   170.6  2963.8
   183.3 2956.98   217.1 2927.75   237.1 2911.73   241.1 2910.24   261.1 2908.92
  266.812909.967   285.2 2915.75   293.2 2914.44   312.2 2919.99   331.4 2916.09
   349.2 2915.55   365.2 2924.52     402 2952.99   425.4 2966.81   437.5 2970.38
     462 2986.76   489.7 2998.86   529.8 3025.58   545.9 3030.97     585 3034.59
   626.2 3041.81   678.4 3058.18   722.5 3080.92   746.6 3096.42   761.2 3102.32
#Mann= 3 ,-1,0
       0      .1       0   241.1    .045       0  266.81      .1       0
Bank Sta=241.1,266.81
XS Rating Curve= 0 ,0
Exp/Cntr(USF)=0,0
Exp/Cntr=0.3,0.1

Type RM Length L Ch R = 1 ,7700    ,182.6,191.8,194.2
XS GIS Cut Line= 4
2209623.54574649546247.927466477 2209964.0143223546305.919454759
2210037.65695147 546260.839360892210430.21007488546226.362550069
#Sta/Elev= 30
       0 3056.13    49.3 3031.94   110.2 3009.69   158.9    2979   203.5 2957.72
   221.9 2952.63   256.3 2938.82   276.6 2929.63   285.9 2923.05     309  2912.9
   321.2 2909.85   341.5 2908.29   357.7 2899.89     369  2896.2   377.4 2889.82
   392.5 2888.25  399.632889.689   411.2 2895.76   431.7 2909.53   518.6 2959.06
   526.6 2964.94   562.5  2983.1   578.8 2993.26     623 3025.18     639 3031.82
   663.1 3034.15   687.2 3038.68   751.5 3065.54     787 3085.13   825.8  3101.2
#Mann= 3 ,-1,0
       0      .1       0   377.4    .045       0  399.63      .1       0
Bank Sta=377.4,399.63
XS Rating Curve= 0 ,0
Exp/Cntr=0.3,0.1

Type RM Length L Ch R = 1 ,7508    ,135,135.5,137.9
XS GIS Cut Line= 4
2209594.39902651546411.0099572182209963.15306875546469.700473565
2210060.44064318546465.8552225192210440.85843858 546421.89184522
#Sta/Elev= 30
       0 3061.06    38.3 3046.61    50.4 3039.43    78.8 3027.04   115.2 3016.22
   155.7 3000.66   167.9 2994.36   196.2  2987.2   216.5 2978.61   265.1 2948.26
   293.4 2925.45   321.4 2907.66     342 2896.95   358.2 2890.81   374.4 2881.62
   410.4 2876.02   414.4 2875.13   428.1 2876.08   446.5 2878.98   458.5 2875.92
   466.5 2879.02   494.7 2896.04   543.3 2933.97   619.5 2978.71   647.2 2998.53
   702.1 3018.68   756.4 3044.86   800.7 3076.01     845 3096.26   853.7 3102.05
#Mann= 3 ,-1,0
       0      .1       0   410.4    .045       0   428.1      .1       0
Bank Sta=410.4,428.1
XS Rating Curve= 0 ,0
Exp/Cntr(USF)=0,0
Exp/Cntr=0.3,0.1

Type RM Length L Ch R = 1 ,7373    ,270.5,277.2,275.5
XS GIS Cut Line= 4
2209574.86162002546509.8401795042209976.63419051 546591.49835536
2210093.08315558546595.6443570862210488.81768759546537.034159155
#Sta/Elev= 30
       0 3048.47    62.6 3024.99    99.3 3016.68   119.3 3008.22   205.4  2989.5
   270.7  2956.9   323.8 2933.52     333 2927.41   368.7 2896.14   405.4 2872.38
   445.6 2865.84   465.6 2867.33   473.6  2865.5   474.2 2865.33   485.6 2863.23
   496.2 2865.66   517.6 2882.13   552.5 2915.13   578.2 2932.01   594.3 2940.74
   602.4 2942.37   663.1 2977.26   675.2 2981.43   727.8 3010.91   739.9 3014.54
   776.3 3033.51   813.2  3053.8   849.1 3076.84   881.4 3089.79   926.6 3113.47
#Mann= 3 ,-1,0
       0      .1       0   473.6    .045       0   496.2      .1       0
Bank Sta=474.2,496.2
XS Rating Curve= 0 ,0
Exp/Cntr=0.3,0.1

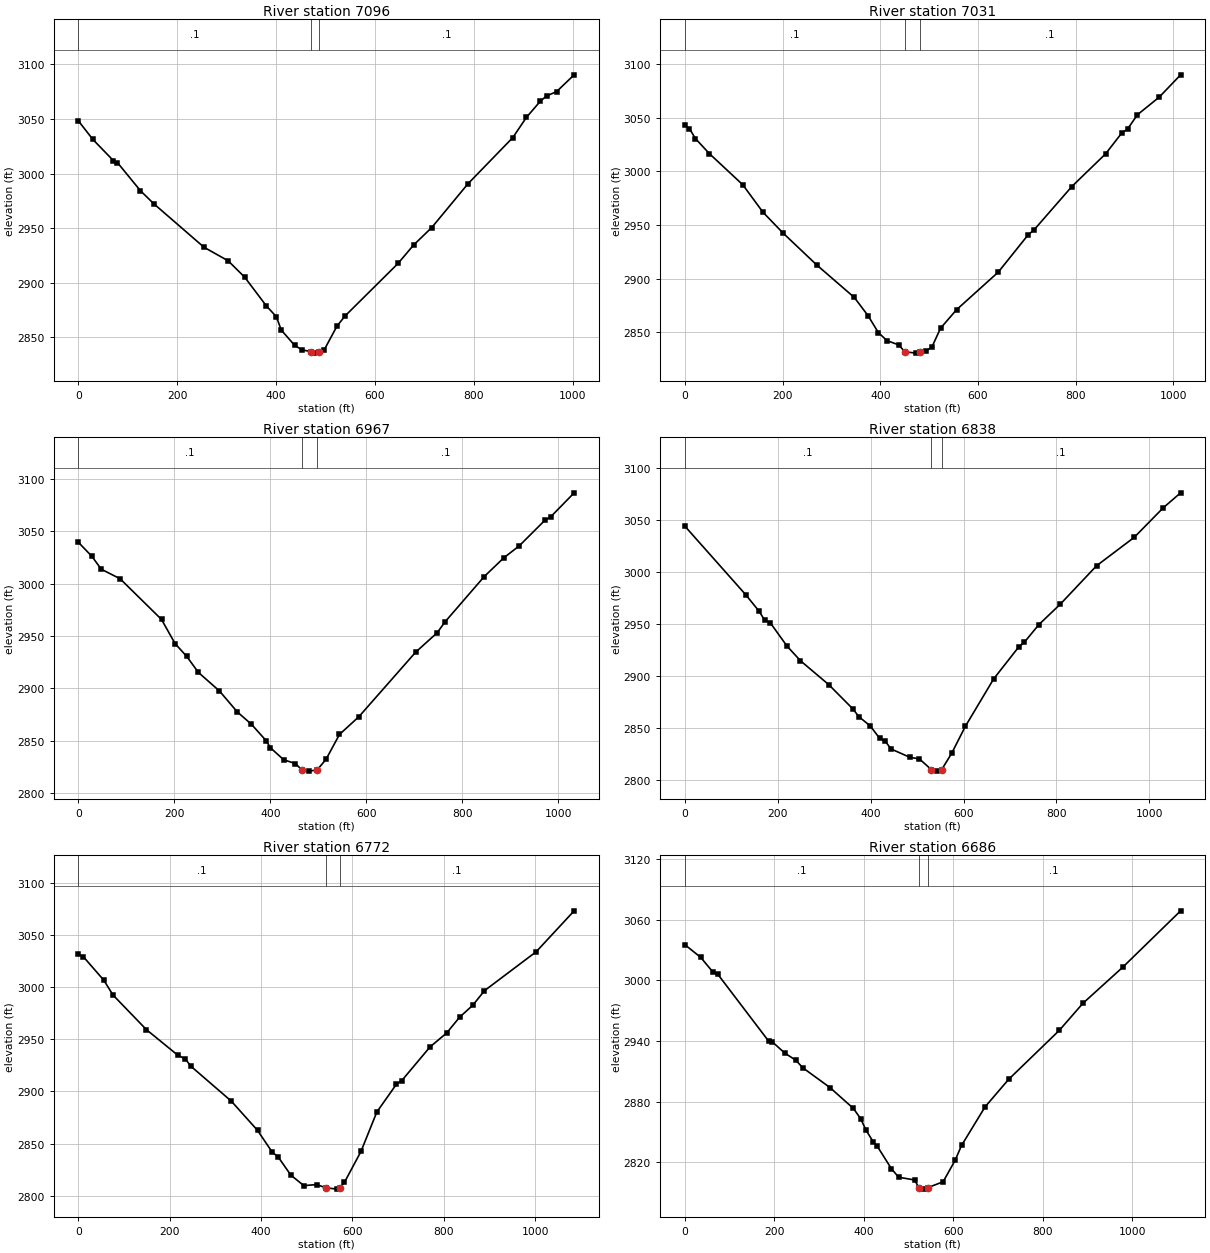
Type RM Length L Ch R = 1 ,7096    ,78.8,64.4,56.9
XS GIS Cut Line= 4
2209546.29442215546708.7547950782209953.69110637546784.330699629
2210030.43996324546840.1490496032210515.11668866546746.708890871
#Sta/Elev= 30
       0 3048.25    29.4 3031.18    71.1 3011.73    79.2 3009.93   125.5  2984.3
   152.4  2972.4   254.1 2932.51     303 2920.08   336.5 2905.06   380.3 2878.77
   400.6 2868.84   410.3 2856.75   437.2  2842.8     452 2838.57  470.542836.917
   476.9 2835.55   486.7 2836.87   496.9  2838.2   523.2 2860.36   539.5 2869.59
   646.5 2917.61     678 2934.48   714.8 2950.54     788 2990.58   878.7 3032.88
   906.4 3051.47   934.7 3066.35     947    3071   967.3    3075  1002.8 3090.35
#Mann= 3 ,-1,0
       0      .1       0  470.54    .045       0   486.7      .1       0
Bank Sta=470.54,486.7
XS Rating Curve= 0 ,0
Exp/Cntr(USF)=0,0
Exp/Cntr=0.3,0.1

Type RM Length L Ch R = 1 ,7031    ,59.8,64.5,66.5
XS GIS Cut Line= 5
2209530.84644684546795.4870476822209916.75042444546865.348974662
2209963.57159597546887.9753856452210052.08489429546864.939460478
2210522.98452068546777.649439815
#Sta/Elev= 30
       0 3043.22     9.5    3040    21.7 3030.71    50.1 3016.73   118.7 2987.56
   159.9 2962.01   200.5 2942.79   269.6 2912.93   346.9 2882.44   375.3 2865.26
     396 2849.71   413.8 2842.18   437.8  2838.2  450.31 2831.74   473.7 2830.52
  480.742831.705   494.4 2832.72     506 2836.49   523.3 2853.74     556 2870.97
   641.5 2906.11   702.5 2940.83   714.7 2945.52     792 2985.95   861.2  3016.5
   893.7 3035.61   906.2  3039.7   926.3 3052.95     971 3069.43  1014.6 3090.15
#Mann= 3 ,-1,0
       0      .1       0  450.31    .045       0  480.74      .1       0
Bank Sta=450.31,480.74
XS Rating Curve= 0 ,0
Exp/Cntr(USF)=0,0
Exp/Cntr=0.3,0.1

Type RM Length L Ch R = 1 ,6967    ,131.6,129.1,123.7
XS GIS Cut Line= 4
2209520.89077755546885.2928481262209924.63607929546947.200461061
 2210076.0154263546940.4177937992210540.26765518546849.420206229
#Sta/Elev= 30
       0  3039.5      28 3026.19    47.8 3013.78      87 3004.67   173.3 2965.83
   201.6 2942.75   225.9  2930.5   250.2 2915.22     294 2897.56   331.1 2877.61
   360.7 2865.75   391.8 2849.84   399.9 2843.45     428 2831.84     452 2828.31
  465.972822.215   480.1 2821.03  497.442822.129   516.1 2832.27   544.1 2856.04
   584.6    2873   702.8 2934.55   747.7 2953.14     764 2963.48   845.5 3006.65
   886.2 3024.52   918.9 3036.17   971.8 3060.34   984.1 3063.72  1033.1 3086.69
#Mann= 3 ,-1,0
       0      .1       0  465.97    .045       0  497.44      .1       0
Bank Sta=465.97,497.44
XS Rating Curve= 0 ,0
Exp/Cntr(USF)=0,0
Exp/Cntr=0.3,0.1

Type RM Length L Ch R = 1 ,6838    ,62.3,66.2,65.9
XS GIS Cut Line= 4
 2209510.8242036546984.0944221322210005.18789529547070.226753172
2210083.17912407547050.5649887282210556.98753168546946.954133764
#Sta/Elev= 30
       0 3044.13   131.3 2977.94   159.7 2962.24   171.9 2953.53   184.1 2950.95
   219.9 2928.58     249 2914.41   309.9  2891.4   361.7 2868.06   374.9 2860.48
   399.3 2851.57   419.6 2839.59   431.8 2836.72   443.9 2829.48   484.5 2821.41
   504.9 2819.92  530.642809.588     542 2808.12  552.872809.561   574.3  2825.2
   603.7 2851.11   664.9 2897.02   718.6 2927.62   730.7 2932.18   762.3 2949.32
   808.5 2969.04   886.3 3005.92   967.3 3033.26  1029.6 3061.66  1067.2 3076.16
#Mann= 3 ,-1,0
       0      .1       0  530.64    .045       0  552.87      .1       0
Bank Sta=530.64,552.87
XS Rating Curve= 0 ,0
Exp/Cntr(USF)=0,0
Exp/Cntr=0.3,0.1

Type RM Length L Ch R = 1 ,6772    ,71.8,85.5,86.8
XS GIS Cut Line= 4
2209509.26217462547050.2766933982209994.40064797547130.858139828
2210121.83313342547113.7613356232210577.74795447547022.774198112
#Sta/Elev= 30
       0 3031.31    11.1 3028.97    55.7 3006.57    75.9 2992.33   148.9 2959.22
   217.9 2934.59   234.1 2931.16   246.2 2924.17   335.1 2890.55   392.2 2862.66
   424.7 2841.55   436.8 2837.55   465.2 2819.73   493.6 2809.69   521.8 2810.71
   541.1  2807.7     566 2806.33   573.1 2807.75   582.4 2812.76   618.7 2842.45
   653.4 2880.25   696.2 2906.82   707.9 2910.29   769.6 2942.49   806.5 2956.09
   834.8 2971.21   863.4 2982.53     889  2996.5  1002.1 3033.77  1085.3 3073.02
#Mann= 3 ,-1,0
       0      .1       0   541.1    .045       0   573.1      .1       0
Bank Sta=541.1,573.1
XS Rating Curve= 0 ,0
Exp/Cntr(USF)=0,0
Exp/Cntr=0.3,0.1

Type RM Length L Ch R = 1 ,6686    ,108.5,108,108
XS GIS Cut Line= 4
2209498.74672538547116.4815446862209987.45580715547182.175343463
2210087.25217823547211.8430109192210591.93613761547133.213238249
#Sta/Elev= 30
       0 3035.48    35.3 3022.95      62 3008.78    74.1 3005.93   187.1 2940.09
   195.2 2939.37   223.4 2928.11     248 2921.08   263.8 2913.54   324.3 2894.03
   376.8 2873.32   392.9 2863.25     405 2851.86   421.2 2840.13   429.3 2836.45
   461.5 2813.83   477.7 2805.28   513.5 2802.51   523.1 2794.92   535.6 2793.46
  543.152794.944   577.3 2800.76   603.9 2821.82   618.4 2836.66     671 2874.87
   723.6 2902.07     837 2950.64   889.6 2977.37   978.8 3013.17    1108 3068.93
#Mann= 3 ,-1,0
       0      .1       0   523.1    .045       0  543.15      .1       0
Bank Sta=523.1,543.15
XS Rating Curve= 0 ,0
Exp/Cntr=0.3,0.1

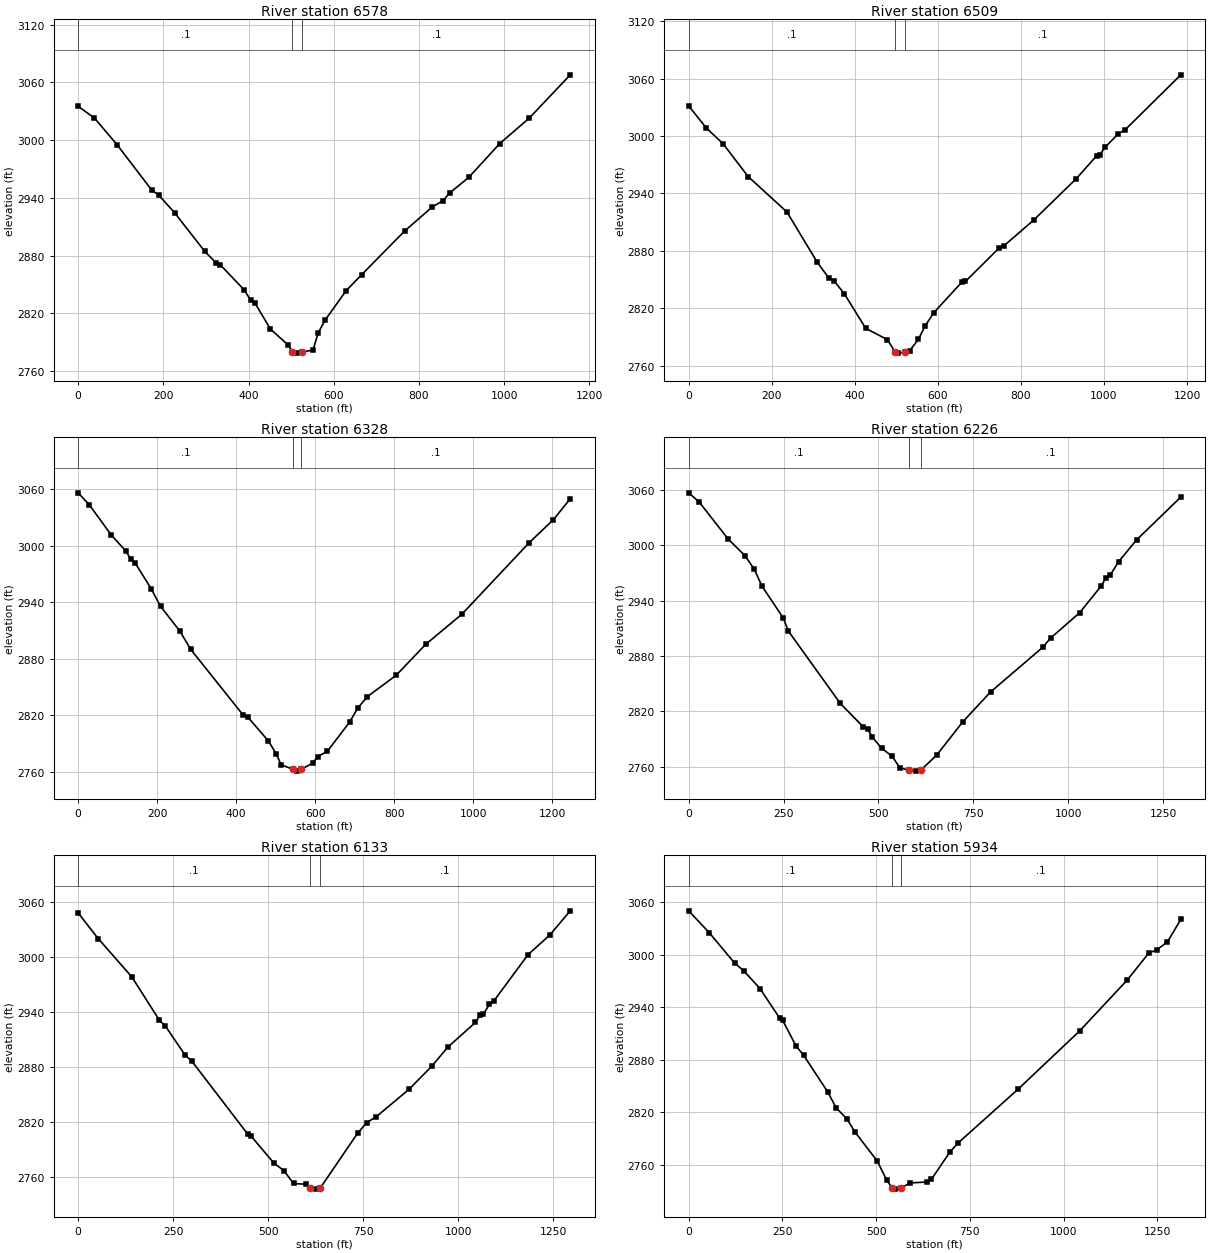
Type RM Length L Ch R = 1 ,6578    ,70,69.5,68.4
XS GIS Cut Line= 4
2209474.95916299 547177.396486642209937.09580997547277.099436716
2210027.06940328547304.2238614152210607.22199082547206.008291397
#Sta/Elev= 30
       0 3035.09    38.1 3022.99    91.3 2995.25   172.5 2948.22   189.5 2942.79
   226.4 2924.57     297 2884.57   324.5 2872.16   334.1  2870.3     390 2844.39
   404.7 2833.96   414.8 2830.95   451.4 2803.82   492.7 2787.34  502.98  2780.4
   513.6 2778.82   526.1 2780.29   551.2 2781.81   563.7 2799.99     580 2813.32
   628.7 2843.43   665.2 2860.14   766.7 2905.72   831.6 2930.72   855.9 2936.87
   872.1 2945.12   916.8 2961.19   989.8 2996.48  1058.8 3022.76  1155.2 3067.79
#Mann= 3 ,-1,0
       0      .1       0  502.98    .045       0   526.1      .1       0
Bank Sta=502.98,526.1
XS Rating Curve= 0 ,0
Exp/Cntr(USF)=0,0
Exp/Cntr=0.3,0.1

Type RM Length L Ch R = 1 ,6509    ,182.3,180.9,175.8
XS GIS Cut Line= 4
2209458.21295104 547280.092591452209921.47327883547347.334161658
2210015.37516859547368.5224874992210628.81037191547274.432739473
#Sta/Elev= 30
       0 3031.59    42.4 3008.45    82.8 2991.97   143.4 2957.56   236.4 2920.71
   309.8 2867.86   337.5 2851.55   349.6 2848.73   374.6 2835.25   426.2 2798.99
   478.6 2787.12  497.132774.304   503.7 2773.06  521.012774.224   532.4 2775.77
   552.9 2787.32   569.2 2801.37   589.5    2815   658.3 2847.59   666.4 2848.03
   747.3 2882.89   759.4 2885.38   831.2 2912.36   933.4 2955.54     982 2979.25
   990.1 2980.41  1002.2  2988.2  1034.6 3002.42  1050.8 3006.55    1185 3064.06
#Mann= 3 ,-1,0
       0      .1       0  497.13    .045       0  521.01      .1       0
Bank Sta=497.13,521.01
XS Rating Curve= 0 ,0
Exp/Cntr(USF)=0,0
Exp/Cntr=0.3,0.1

Type RM Length L Ch R = 1 ,6328    ,112.2,101.6,95.6
XS GIS Cut Line= 4
2209404.40767415547487.0300502292209913.73907116547531.340574724
2209996.28756101547527.0787461142210638.53292945547418.756127684
#Sta/Elev= 30
       0 3055.98    27.9 3043.47    84.1 3011.15     120  2994.6   133.7 2985.39
   144.3 2981.56   184.5 2954.56   208.6 2935.56   256.7 2909.88   284.8 2890.08
   417.3 2820.54   429.4 2818.25   481.6 2792.91   501.7 2778.89   513.7 2767.74
  544.852762.827   553.7 2761.03  564.322762.873   593.9 2769.67     606 2776.47
   630.5 2781.96   687.1 2813.12   707.4 2827.75   731.7 2839.95   804.7  2862.6
   879.3 2895.36   971.1 2927.38  1141.4 3003.19  1202.3 3027.41  1245.2 3049.65
#Mann= 3 ,-1,0
       0      .1       0  544.85    .045       0  564.32      .1       0
Bank Sta=544.85,564.32
XS Rating Curve= 0 ,0
Exp/Cntr=0.3,0.1

Type RM Length L Ch R = 1 ,6226    ,82.8,92.9,100.5
XS GIS Cut Line= 4
 2209393.0212646547568.4516723442209948.58992201547645.798805787
2210018.18224556547594.2604183752210659.29794216547492.829821955
#Sta/Elev= 30
       0 3056.99    27.4 3047.17   104.1 3006.78   148.6 2988.77   172.8 2974.09
     193 2955.85   249.5 2921.05   261.7 2907.64     399 2828.84   459.5 2803.37
   471.7 2800.61   483.8 2792.06     508 2780.18   536.3  2771.2   556.5 2758.75
  579.412756.358   598.2 2755.22  611.592756.315   653.7 2772.74   722.4  2808.8
   795.3 2841.07     933 2889.54   953.3 2899.38  1030.2 2927.04  1086.9    2956
  1099.1 2964.55  1111.2  2968.1  1132.7 2982.37  1180.1 3005.95  1296.6 3052.39
#Mann= 3 ,-1,0
       0      .1       0  579.41    .045       0  611.59      .1       0
Bank Sta=579.41,611.59
XS Rating Curve= 0 ,0
Exp/Cntr(USF)=0,0
Exp/Cntr=0.3,0.1

Type RM Length L Ch R = 1 ,6133    ,197.9,198.7,196.7
XS GIS Cut Line= 4
2209391.40487213547664.2865802152209932.58383304547708.075013578
2210054.02864575547706.7876127372210673.28095672547590.131891113
#Sta/Elev= 30
       0 3047.96    52.9 3019.86   141.2 2978.09   213.8 2930.75   229.5 2924.41
   281.7 2892.47   298.6 2886.32   446.2 2806.35   454.5 2804.42   514.4 2774.97
   541.3 2766.47   566.5 2752.53   598.5 2751.62   610.5 2747.36   626.5 2746.33
   636.6 2747.36   735.3 2807.49   759.5 2819.09   784.6 2825.53   870.1 2855.23
   931.2 2880.99   971.9 2901.18  1045.1 2928.37  1057.3 2936.32  1065.5 2937.04
  1081.8 2948.09    1094 2952.08  1183.5 3002.44  1240.5 3023.78  1294.5 3050.26
#Mann= 3 ,-1,0
       0      .1       0   610.5    .045       0   636.6      .1       0
Bank Sta=610.5,636.6
XS Rating Curve= 0 ,0
Exp/Cntr(USF)=0,0
Exp/Cntr=0.3,0.1

Type RM Length L Ch R = 1 ,5934    ,211.5,212.3,220.4
XS GIS Cut Line= 4
2209401.70991999 547865.388876222209925.45951972547883.166277777
2210051.36237124  547869.96948092210694.89537627547716.332201621
#Sta/Elev= 30
       0 3049.92    54.5 3025.09   122.5 2990.18   146.5 2981.55   190.6 2960.83
   242.6 2927.28   250.6 2924.76   286.6 2895.28   306.6 2884.84   370.7 2843.02
   393.1 2824.94   422.7 2811.75   442.7 2797.62   502.8 2764.08   528.3 2742.03
   542.8 2733.26   550.9 2731.97  566.032733.271   591.1  2739.1   635.4 2740.06
   647.4 2743.25   696.7  2774.5   717.3 2784.25   877.7 2845.89  1042.2 2912.56
  1169.9 2971.07  1227.2 3001.81  1247.8 3005.17  1276.6 3014.44  1312.3 3040.05
#Mann= 3 ,-1,0
       0      .1       0   542.8    .045       0  566.03      .1       0
Bank Sta=542.8,566.03
XS Rating Curve= 0 ,0
Exp/Cntr(USF)=0,0
Exp/Cntr=0.3,0.1

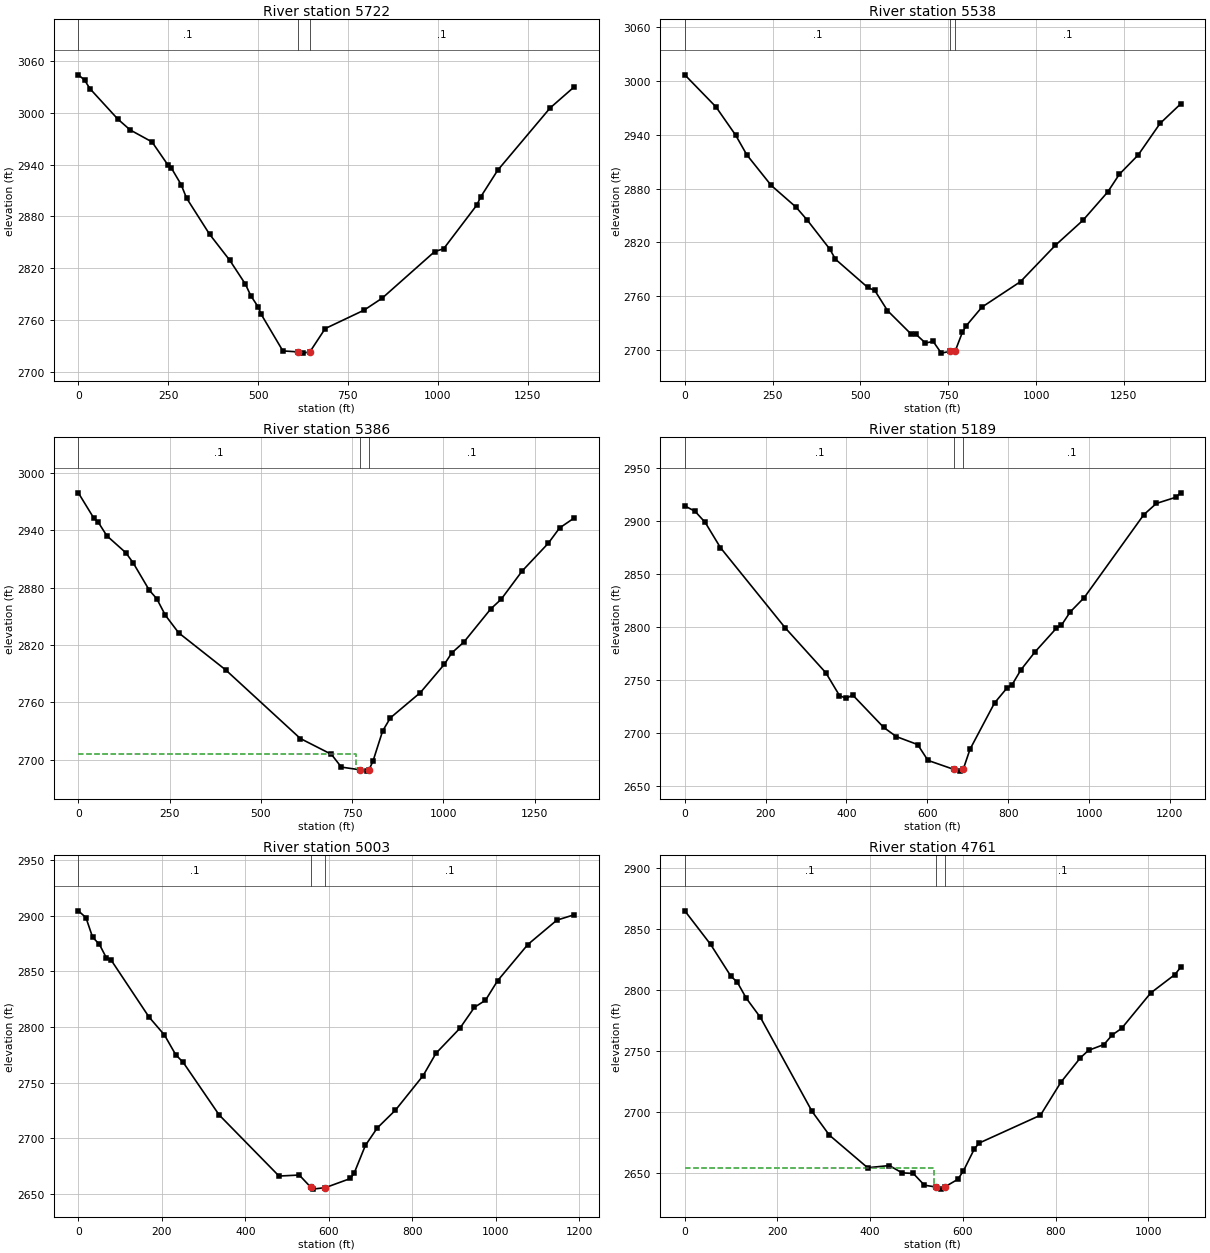
Type RM Length L Ch R = 1 ,5722    ,190.1,184.6,165.4
XS GIS Cut Line= 5
2209395.35804738548002.6777756392209529.85608867548070.682726956
 2209940.2951587548075.4443402092210046.65238744548089.517532878
2210728.06419575547886.151662801
#Sta/Elev= 30
       0 3043.75    17.4 3037.66    32.2 3027.79   109.6 2992.65   144.3 2979.99
     205 2966.16     249 2939.62   258.3 2936.33     286 2916.83     301 2901.27
     365 2859.47   421.7 2829.06   465.1 2801.51   479.7 2788.38   501.1 2774.85
   509.1 2766.57   569.1 2724.43  610.892723.346   625.6 2721.88  644.452723.417
   686.8 2750.25   795.2 2771.62   845.4 2785.44   991.3 2839.26  1016.5 2842.61
  1108.4 2892.94    1120 2902.82  1166.8 2933.37  1312.8 3005.47  1379.6 3029.76
#Mann= 3 ,-1,0
       0      .1       0  610.89    .045       0  644.45      .1       0
Bank Sta=610.89,644.45
XS Rating Curve= 0 ,0
Exp/Cntr=0.3,0.1

Type RM Length L Ch R = 1 ,5538    ,148.4,151.1,153.4
XS GIS Cut Line= 4
2209331.57131129548304.0611199992210027.18498741548276.687448192
2210108.52713431548201.1067500882210692.80981476548045.996239422
#Sta/Elev= 30
       0 3006.45    88.7  2970.8   144.7  2939.4   176.7 2917.37     246 2883.47
   316.8 2859.25   348.9 2844.74   412.9 2812.55   428.9 2801.35     521 2769.92
     541 2766.56     577 2744.23   643.5 2718.39   657.1 2718.18   685.1 2708.15
   707.2 2709.85   730.3 2696.88  754.772698.817  769.572698.845   790.3 2720.02
   801.2 2727.26   846.1 2748.08   955.8 2776.38  1055.1 2816.82  1133.8  2844.7
  1204.1 2876.11  1237.2 2895.82  1290.9 2917.29  1353.1 2952.34  1411.7 2974.06
#Mann= 3 ,-1,0
       0      .1       0  754.77    .045       0  769.57      .1       0
Bank Sta=754.77,769.57
XS Rating Curve= 0 ,0
Exp/Cntr(USF)=0,0
Exp/Cntr=0.3,0.1

Type RM Length L Ch R = 1 ,5386    ,191,197.7,202.1
XS GIS Cut Line= 4
2209398.43148982548456.0057080562210104.12511291548386.786955551
2210219.65289084 548321.130366252210723.15528989548207.067219093
#Sta/Elev= 30
       0 2978.85    41.9 2952.73      54 2948.47    78.1 2934.01   130.4  2916.2
   150.5 2905.56   194.5 2877.12   214.8 2868.34   238.4 2851.07   274.8 2832.71
   403.7 2793.97   608.1 2722.38   693.1 2705.91   720.4 2692.53  771.342689.741
   789.5 2688.33  796.032689.718   807.1 2698.68   833.5 2730.18   854.8 2743.95
   936.8 2770.27  1002.9 2799.97    1023 2811.74  1055.8 2822.91  1129.9 2857.73
  1158.3 2867.76  1215.7 2897.22  1287.1 2926.09  1318.3 2942.17  1358.2 2952.56
#Mann= 3 ,-1,0
       0      .1       0  771.34    .045       0  796.03      .1       0
#XS Ineff= 2 , 0
          759.39 2706.41
Permanent Ineff=
       F       F
Bank Sta=771.34,796.03
XS Rating Curve= 0 ,0
Exp/Cntr(USF)=0,0
Exp/Cntr=0.3,0.1

Type RM Length L Ch R = 1 ,5189    ,206.3,186,171.8
XS GIS Cut Line= 4
2209584.15164972548724.3487935962210157.55670301548538.297754443
2210263.78743592548532.4519677542210739.26812895548328.527454349
#Sta/Elev= 30
       0 2914.41    25.3 2909.36    50.5 2898.79    88.3  2874.9   248.1  2799.3
   349.1  2756.6   382.7 2735.12   399.5 2732.45   415.3 2735.72     492 2705.05
   523.2 2696.38   576.1 2688.82   601.4  2673.9   665.5 2665.37   681.6 2663.72
  688.782665.427   705.6 2684.42   766.2 2728.12   796.7 2742.14   809.8 2745.48
   831.5 2759.46   866.3 2776.37   919.1 2798.74   931.6 2801.53   953.4 2814.16
   988.2 2827.79  1135.4 2906.07  1166.6 2916.76  1214.5 2922.55  1226.6 2926.79
#Mann= 3 ,-1,0
       0      .1       0   665.5    .045       0  688.78      .1       0
Bank Sta=665.5,688.78
XS Rating Curve= 0 ,0
Exp/Cntr=0.3,0.1

Type RM Length L Ch R = 1 ,5003    ,222,241.6,248.5
XS GIS Cut Line= 4
2209706.86648695548873.619230542 2210213.0353437548760.591458085
2210298.09143673548614.5029070792210753.73107468548407.819341111
#Sta/Elev= 30
       0 2904.45    18.2 2898.38    34.1 2880.82    50.5 2874.29    66.9 2862.39
    79.2 2859.85   169.4 2808.97   206.3 2792.87   233.3 2775.16   251.3 2768.22
   337.4 2721.01   480.9 2666.07   529.3    2667  557.47 2655.82   561.5 2654.33
     592 2655.69   652.1  2663.9   661.4 2669.15   687.7 2693.57   716.3 2709.32
   759.8 2725.31   826.2 2756.38   856.9 2776.43   913.9 2798.75   949.1 2817.75
   975.5 2824.06  1004.5 2841.59    1077 2874.17  1146.5 2896.06    1188  2900.9
#Mann= 3 ,-1,0
       0      .1       0  557.47    .045       0     592      .1       0
Bank Sta=557.47,592
XS Rating Curve= 0 ,0
Exp/Cntr(USF)=0,0
Exp/Cntr=0.3,0.1

Type RM Length L Ch R = 1 ,4761    ,181.7,180.1,168.1
XS GIS Cut Line= 4
2209826.24964646548988.807973619 2210286.6004027548870.171389593
2210439.29467798 548870.696804612210777.73440273548586.781962047
#Sta/Elev= 30
       0 2864.69    55.7 2837.17    99.8 2810.91   112.9 2806.46   132.6  2793.1
   163.1 2777.38   274.6 2700.32   311.8 2680.93   394.4  2654.2   441.4 2655.95
   468.8 2649.98     493 2649.49     517 2639.87     541 2638.46     553 2636.65
     561 2638.45     589 2644.68     601 2651.47     625  2669.8   635.5 2674.47
   767.4 2697.22   811.5 2724.24   853.7 2744.34   871.1 2750.37   904.3 2755.12
   922.2 2762.97   942.5 2768.37  1005.2 2797.35  1057.4 2812.46  1069.8 2818.38
#Mann= 3 ,-1,0
       0      .1       0     541    .045       0     561      .1       0
#XS Ineff= 2 , 0
          538.37 2653.64
Permanent Ineff=
       F       F
Bank Sta=541,561
XS Rating Curve= 0 ,0
Exp/Cntr=0.3,0.1