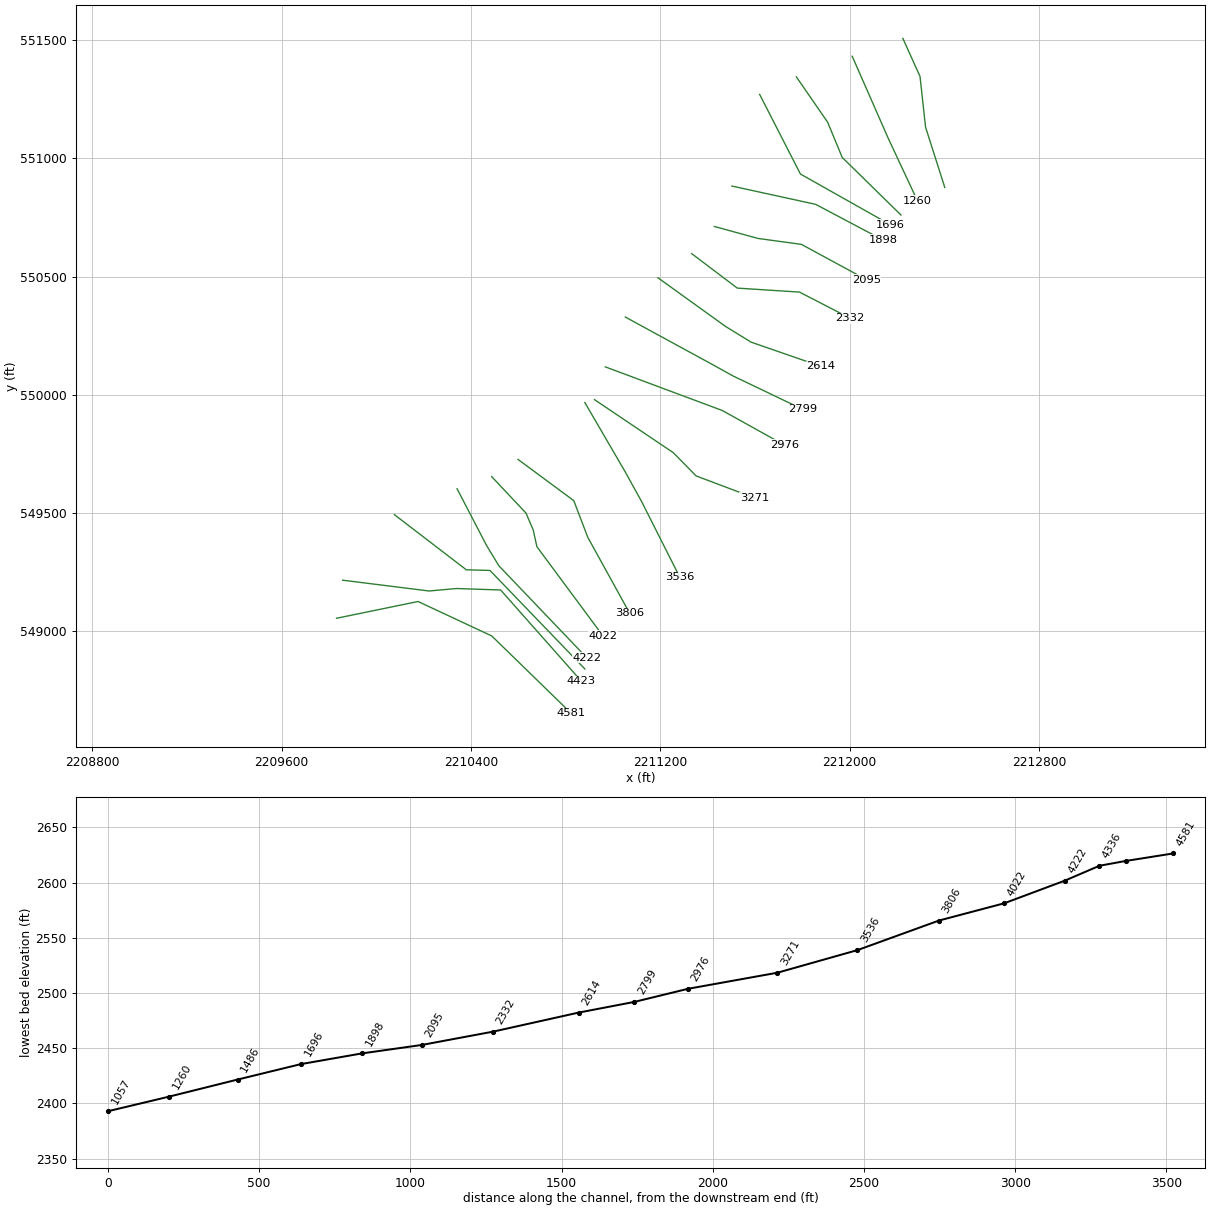
HEC-RAS study CHIMRCKRN.prj: CHIMRCKRN

--- CHIMRCKRN.g01 (geometry) --- (continued)

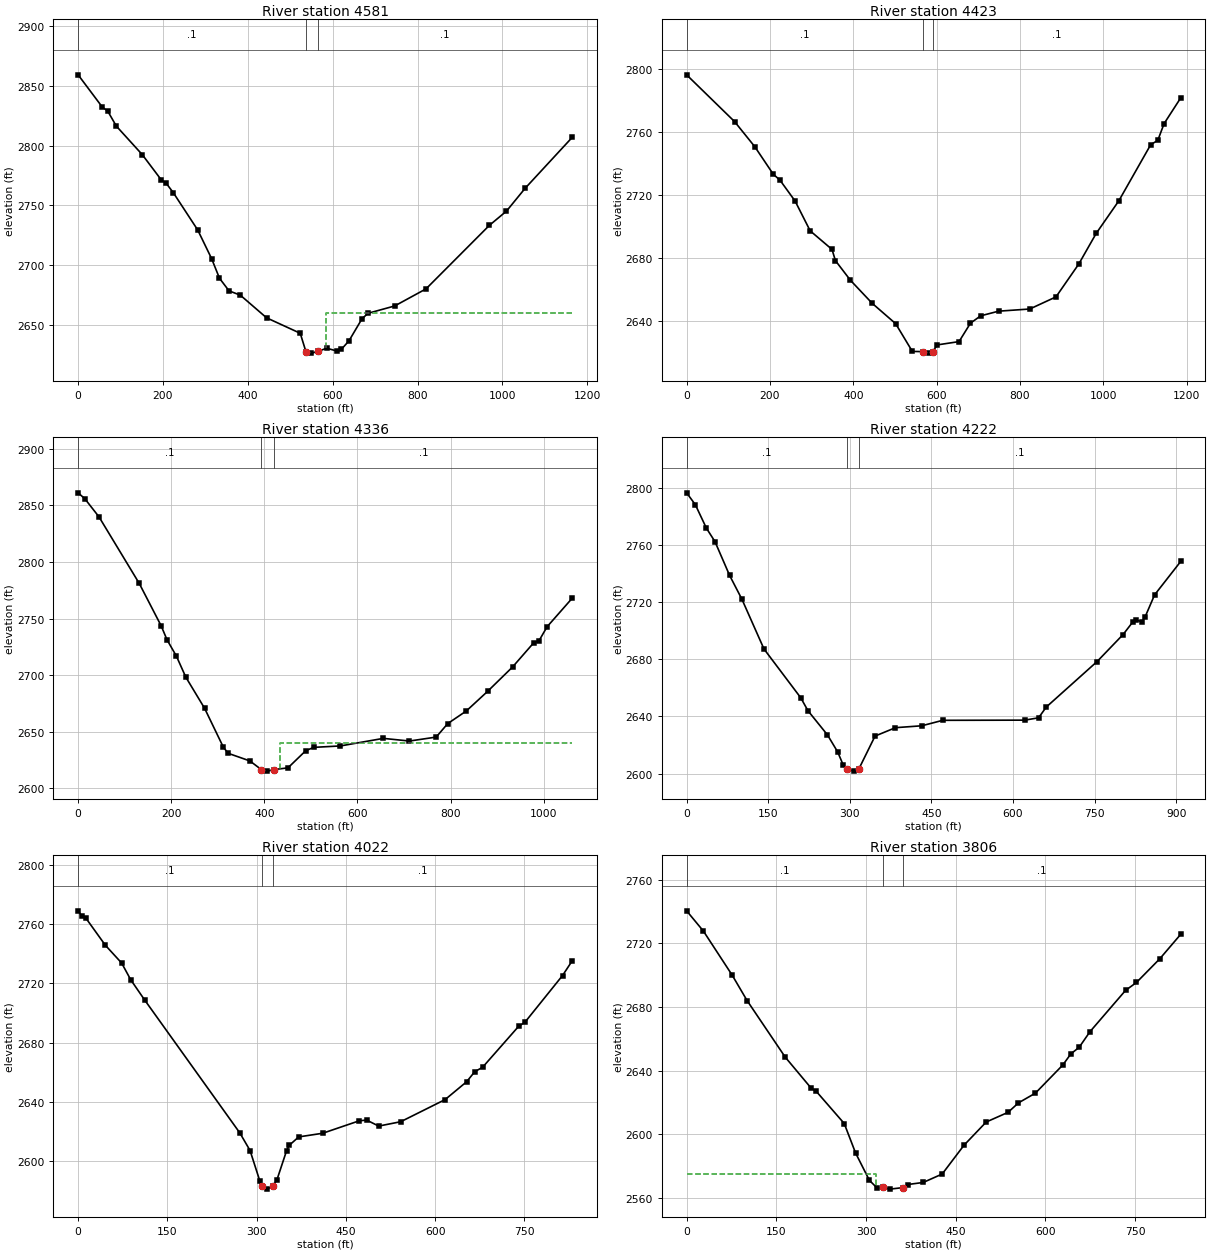
Type RM Length L Ch R = 1 ,4581    ,155,158.3,163.2
XS GIS Cut Line= 4
2209832.02089269549055.808152323 2210176.5005933549126.664560495
2210487.96645378548981.042570727 2210823.9324455548653.826583211
#Sta/Elev= 30
       0 2859.25    57.3 2832.11    69.6    2829      90 2816.37   151.3 2792.42
   196.2 2771.25   207.9 2768.39   224.7 2760.44   281.9  2729.4   314.6 2705.45
   333.2    2689   355.7 2678.47   382.2  2674.9   444.1 2655.93   523.5 2642.99
   536.8  2627.7     550 2626.37  565.542627.749   585.4 2630.51   611.3 2628.02
   620.7 2629.67   638.4 2636.67   669.3 2655.26   683.5 2659.72   746.1 2665.84
     820 2680.15   969.4 2733.34  1009.6 2745.21  1053.2 2764.17  1164.5 2806.92
#Mann= 3 ,-1,0
       0      .1       0   536.8    .045       0  565.54      .1       0
#XS Ineff= 2 , 0
                             585            2660
Permanent Ineff=
       F       F
Bank Sta=536.8,565.54
XS Rating Curve= 0 ,0
Exp/Cntr(USF)=0,0
Exp/Cntr=0.3,0.1

Type RM Length L Ch R = 1 ,4423    ,88.5,86.4,86.4
XS GIS Cut Line= 5
2209857.92787891549216.715630897 2210223.4475877549171.004417305
2210337.77370957549181.4896464182210525.47675226549175.310122379
2210866.61303521548789.981493966
#Sta/Elev= 30
       0 2796.04   115.1 2766.37   163.5 2750.48   207.9    2733     224 2729.24
   260.3 2715.98   296.5 2697.07   348.9 2685.29     357 2678.21   393.1 2665.72
   445.4 2651.08   501.6 2638.19   541.6  2620.6   567.2 2620.45   580.5 2619.51
   590.4 2620.43   601.6 2624.74   653.7 2626.82   681.1 2638.51   705.6 2643.17
   748.6 2646.12   823.4  2647.5   886.3 2655.18   940.8 2675.95   982.8 2695.46
  1037.1 2716.12  1113.6 2751.73  1130.6 2754.47  1145.7 2765.08  1185.6 2781.41
#Mann= 3 ,-1,0
       0      .1       0   567.2    .045       0   590.4      .1       0
Bank Sta=567.2,590.4
XS Rating Curve= 0 ,0
Exp/Cntr(USF)=0,0
Exp/Cntr=0.3,0.1

Type RM Length L Ch R = 1 ,4336    ,126.6,113.9,99.3
XS GIS Cut Line= 4
 2210076.5950916549493.6371427112210380.52980227549260.596757682
2210480.34242292 549257.942518642210881.59214723548841.411878519
#Sta/Elev= 30
       0 2861.01    14.3 2855.85    44.8 2839.79   131.3 2780.97   178.2 2743.65
     191 2731.16   211.2 2716.67   231.3 2698.21   271.7 2670.64     312 2636.27
   322.4 2630.91   368.9  2624.2  393.33 2616.61   406.6 2615.19  421.552616.599
   450.7 2618.08   488.9 2633.24   506.1 2636.18   563.3 2637.44   655.6 2644.11
   711.6 2641.77     769 2645.26   793.9  2657.2   833.8 2668.33   879.3 2685.58
   933.1 2707.18   978.3 2728.46     990 2730.45  1007.3 2742.73  1061.2 2767.94
#Mann= 3 ,-1,0
       0      .1       0  393.33    .045       0  421.55      .1       0
#XS Ineff= 2 , 0
                           432.6            2640
Permanent Ineff=
       F       F
Bank Sta=393.33,421.55
XS Rating Curve= 0 ,0
Exp/Cntr(USF)=0,0
Exp/Cntr=0.3,0.1

Type RM Length L Ch R = 1 ,4222    ,204.1,200.6,197.4
XS GIS Cut Line= 4
2210341.28210117549603.3696206152210465.96222209549363.480575212
 2210518.0672395549277.5527705822210889.35718589548888.981205894
#Sta/Elev= 30
       0 2796.49      16 2788.21    36.4 2771.74    52.1 2762.38    79.1 2738.65
   101.7 2722.01   142.2 2687.25   209.8 2653.11   223.1 2644.02   258.9 2627.13
   277.7 2615.21   288.2 2605.76     294 2603.13   308.6 2601.78   316.4 2603.13
   346.4  2626.3   383.9 2632.18   432.2  2633.5   470.9 2637.33   621.6 2637.45
     647 2639.09   661.2 2646.62   754.5 2678.43   802.4 2697.37   819.7 2705.88
   825.5 2707.56   837.1 2706.31   842.9 2709.73   860.3 2725.11   908.3 2748.47
#Mann= 3 ,-1,0
       0      .1       0     294    .045       0   316.4      .1       0
Bank Sta=294,316.4
XS Rating Curve= 0 ,0
Exp/Cntr=0.3,0.1

Type RM Length L Ch R = 1 ,4022    ,216.3,216.2,215.9
XS GIS Cut Line= 5
2210487.65227939549654.4633091562210632.87715941549500.069067093
2210663.22576992549428.6797427532210678.82243171549358.140944403
2210957.88160541548981.487298137
#Sta/Elev= 30
       0 2769.03     6.6 2765.28    12.6 2764.35    45.7 2745.84    73.2 2733.78
    88.3 2722.59   111.6    2709   271.7 2619.23     289 2607.29   305.4 2586.78
   309.5 2583.15   316.8 2581.24   326.8 2583.25   334.1 2587.42   350.3 2607.06
   354.6 2610.71   370.8 2616.48   411.1 2618.94   472.5 2627.34     485 2627.83
   505.2 2623.78   542.2 2626.72   616.9 2641.67     653 2653.69   666.6 2660.46
   679.9 2663.48   740.3 2691.03   751.3 2693.98   814.2 2725.36   830.5 2735.31
#Mann= 3 ,-1,0
       0      .1       0   309.5    .045       0   326.8      .1       0
Bank Sta=309.5,326.8
XS Rating Curve= 0 ,0
Exp/Cntr(USF)=0,0
Exp/Cntr=0.3,0.1

Type RM Length L Ch R = 1 ,3806    ,265.6,269.5,269.9
XS GIS Cut Line= 4
2210598.87791107 549727.172942662210834.56539844549552.976838035
2210893.85571848549397.8609629312211071.22314373549076.368476993
#Sta/Elev= 30
       0 2740.38    28.1 2727.64    76.2 2699.97   101.1 2684.02   164.9 2648.49
   208.3 2628.99   216.9 2626.96   263.6 2606.78   282.6 2588.24   305.7 2571.09
   318.6 2566.27  328.55 2566.63     340 2565.58  362.492566.561   369.9 2568.48
   395.6 2569.76   427.4 2575.07   463.9 2593.16     501 2607.73   537.6 2613.82
     555 2619.77   583.3 2625.87   629.2 2643.58   642.6 2650.54   656.4 2654.63
   674.6 2664.49     734 2690.38   752.3 2695.38   791.1 2710.17   826.3 2725.62
#Mann= 3 ,-1,0
       0      .1       0  328.55    .045       0  362.49      .1       0
#XS Ineff= 2 , 0
           316.2 2574.97
Permanent Ineff=
       F       F
Bank Sta=328.55,362.49
XS Rating Curve= 0 ,0
Exp/Cntr=0.3,0.1

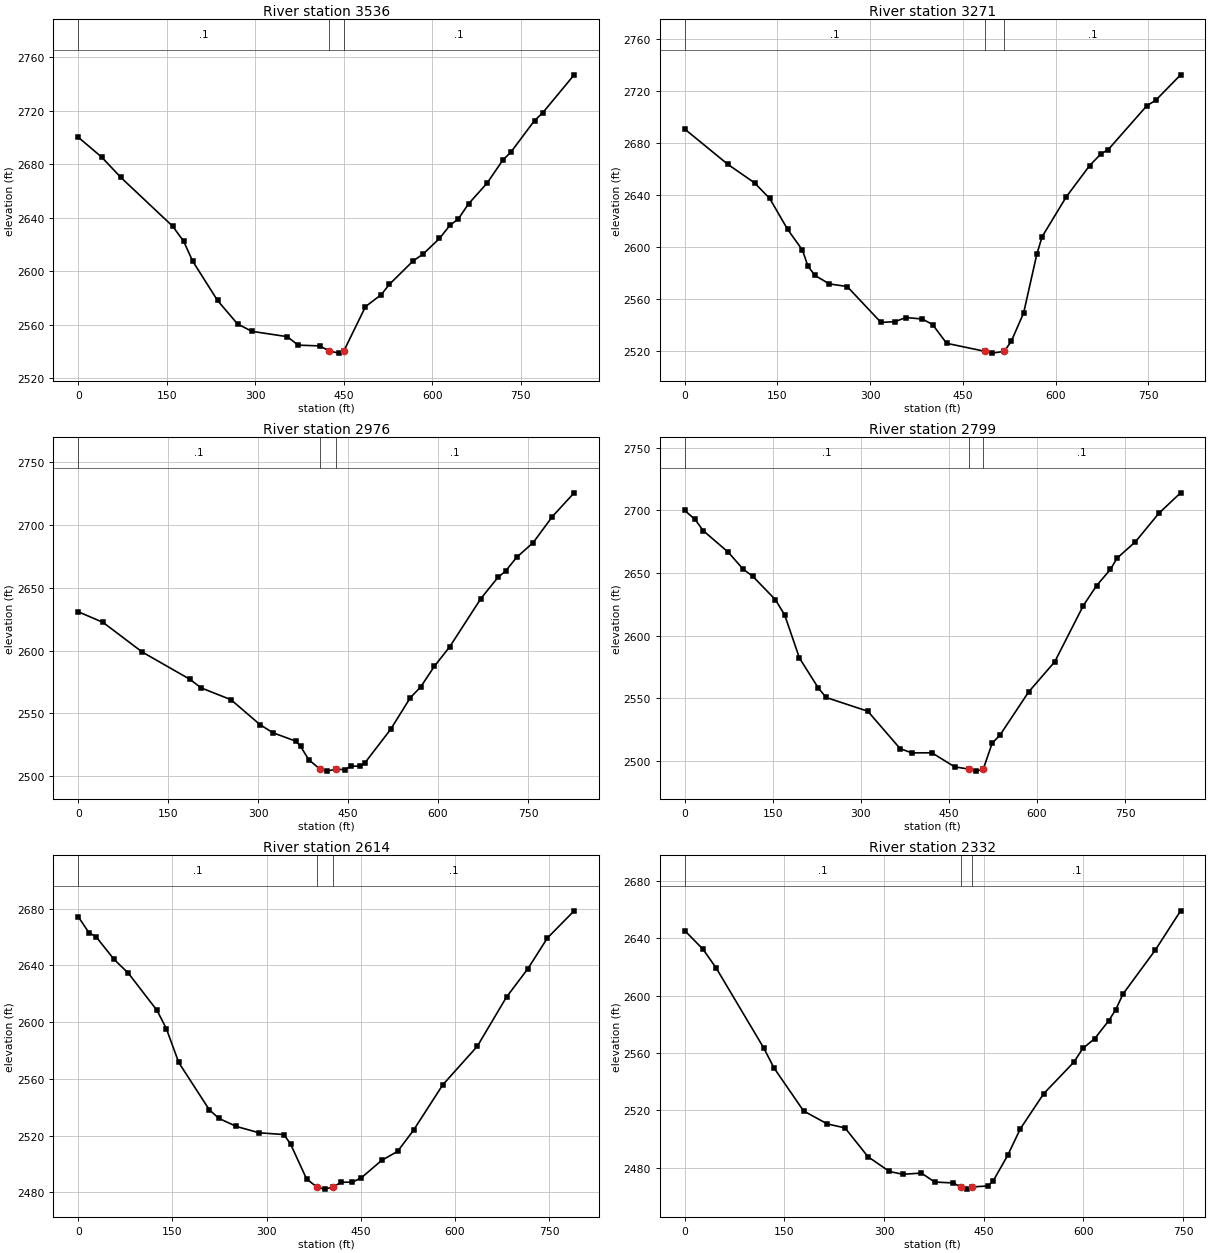
Type RM Length L Ch R = 1 ,3536    ,258.3,265.1,267.9
XS GIS Cut Line= 4
2210881.37979337549967.5740878012211050.48755816549677.082238839
2211120.40664881549550.8385705172211282.52370278549229.453368911
#Sta/Elev= 30
       0  2700.3    39.8 2685.39    72.2 2670.23   160.1 2633.69   178.7 2622.46
   193.9 2607.64   236.1  2578.2     270 2560.62   294.4 2555.11   354.3 2551.13
   372.6 2544.79   409.2 2544.22  424.722540.592   441.2 2538.82   450.3 2540.58
   486.8 2573.59   513.7 2582.63   527.1 2590.16   567.4 2607.73   584.2 2612.81
   612.2 2624.56   630.1 2634.56   643.6 2638.87   661.5  2650.5   692.9 2665.96
   719.7 2683.31   733.2 2689.12   773.3 2712.78   786.9 2718.41   840.4 2746.94
#Mann= 3 ,-1,0
       0      .1       0  424.72    .045       0   450.3      .1       0
Bank Sta=424.72,450.3
XS Rating Curve= 0 ,0
Exp/Cntr(USF)=0,0
Exp/Cntr=0.3,0.1

Type RM Length L Ch R = 1 ,3271    ,285.8,295,300.4
XS GIS Cut Line= 4
2210922.03603087549979.8196141632211255.04997574549755.746367247
2211351.81270536 549657.285199752211597.89975183549564.499342922
#Sta/Elev= 30
       0 2690.61    69.7 2663.51     113 2649.24   137.6  2637.2   166.5  2613.5
   190.6 2597.49   199.4 2585.16   210.9 2578.01     234 2571.54   262.9 2569.53
   317.6 2541.91   340.1 2542.53   357.9 2545.67   384.5 2544.55   401.2 2540.25
   423.8 2525.87  486.53 2519.63   497.3 2518.32   517.1 2519.66   528.4 2527.43
   548.4 2549.22   569.7 2594.27   578.3 2607.82   617.4 2638.46   655.2 2662.52
   673.3 2671.42   685.2 2674.76   747.8 2708.55   762.1  2712.7   802.4 2732.28
#Mann= 3 ,-1,0
       0      .1       0  486.53    .045       0   517.1      .1       0
Bank Sta=486.53,517.1
XS Rating Curve= 0 ,0
Exp/Cntr=0.3,0.1

Type RM Length L Ch R = 1 ,2976    ,180.8,177.2,175.8
XS GIS Cut Line= 3
2210968.09663406 550118.190853962211462.90554601549933.610009882
2211724.01650809 549788.25535463
#Sta/Elev= 30
       0 2630.95    41.3 2622.46   106.8 2598.79     186 2577.12     205 2570.18
   254.7 2560.78   303.2 2540.88   324.5 2534.46     363 2527.65   370.9 2523.51
   384.3 2512.97   403.5 2505.25   414.4  2503.8   429.9 2505.37   444.1 2504.94
   454.6 2507.68   469.7 2507.83   478.2 2510.47   520.9 2537.07   553.7 2562.31
   570.8  2570.8   593.7 2587.27   619.5    2603   671.5 2641.46   699.9 2658.36
   712.7 2663.37     731 2674.29   758.8 2686.16   790.5 2706.77     827  2725.8
#Mann= 3 ,-1,0
       0      .1       0   403.5    .045       0   429.9      .1       0
Bank Sta=403.5,429.9
XS Rating Curve= 0 ,0
Exp/Cntr(USF)=0,0
Exp/Cntr=0.3,0.1

Type RM Length L Ch R = 1 ,2799    ,184.6,184.6,183.6
XS GIS Cut Line= 4
     2211052.622      550328.7082211429.99723722550123.059017712
2211506.41788689550080.5165277452211801.49214366549939.042106014
#Sta/Elev= 30
       0 2699.81    17.7 2692.64    31.4 2683.74    74.2 2666.53    99.7  2652.9
     116 2647.28   154.4 2628.67   170.3 2616.47   195.4 2582.15   227.3 2558.41
   240.9 2550.66   311.9  2539.7   366.8 2509.91   386.7 2506.49     421 2506.56
   459.7 2495.35  484.722493.499   496.4 2491.94  508.362493.459   523.6 2514.23
   536.9 2520.64   585.7 2555.11   630.1 2579.11   678.9    2624   701.3  2639.8
   724.9 2652.78   736.5 2661.88   767.6 2674.85   807.5 2697.58   844.5 2713.87
#Mann= 3 ,-1,0
       0      .1       0  484.72    .045       0  508.36      .1       0
Bank Sta=484.72,508.36
XS Rating Curve= 0 ,0
Exp/Cntr=0.3,0.1

Type RM Length L Ch R = 1 ,2614    ,278.6,282.5,284.5
XS GIS Cut Line= 4
2211190.27835182550494.8930482812211475.39231801550289.531240462
 2211584.0546338550222.7388078232211878.00639967550120.847554818
#Sta/Elev= 30
       0 2674.43    17.1 2663.09    28.4 2660.27      57 2644.35      80 2634.49
   125.6 2608.24   140.4 2595.45   160.1 2571.57   208.9 2538.17   224.2 2532.12
   251.9 2526.46   288.3 2521.97   327.7 2520.76   338.3    2514   363.8 2489.41
   380.5 2483.64   392.9 2482.25   405.5 2483.67   419.1 2487.09   436.8 2487.17
   451.1 2490.27   483.4 2502.55   508.7 2508.85   534.1  2523.8   580.8 2555.87
   635.7    2583   682.3 2617.77   716.1 2637.59   747.5 2659.42     790 2678.54
#Mann= 3 ,-1,0
       0      .1       0   380.5    .045       0   405.5      .1       0
Bank Sta=380.5,405.5
XS Rating Curve= 0 ,0
Exp/Cntr(USF)=0,0
Exp/Cntr=0.3,0.1

Type RM Length L Ch R = 1 ,2332    ,236.2,236.5,234.4
XS GIS Cut Line= 4
2211333.09075211550596.753608677 2211525.4928342550451.205919641
2211788.67495684550434.2585859862212003.00398651550323.540203127
#Sta/Elev= 30
       0 2645.34    27.6  2632.3    47.6 2619.07     119 2563.41   134.3 2549.61
   178.9 2519.54   214.5 2510.51   241.3 2507.69   275.8 2487.62   308.1 2477.32
   328.1 2475.38   356.2  2476.2   376.2 2469.96   404.3 2469.32   415.1  2466.5
   424.3 2465.02   432.3 2466.56   456.4 2467.22   464.4 2470.91   486.2 2488.76
     505 2507.08   540.4 2531.69   585.5 2553.53     599  2563.1     617 2570.02
   638.1 2582.53   648.5 2590.14   659.6 2601.15   707.8 2631.53   746.2  2659.1
#Mann= 3 ,-1,0
       0      .1       0   415.1    .045       0   432.3      .1       0
Bank Sta=415.1,432.3
XS Rating Curve= 0 ,0
Exp/Cntr(USF)=0,0
Exp/Cntr=0.3,0.1

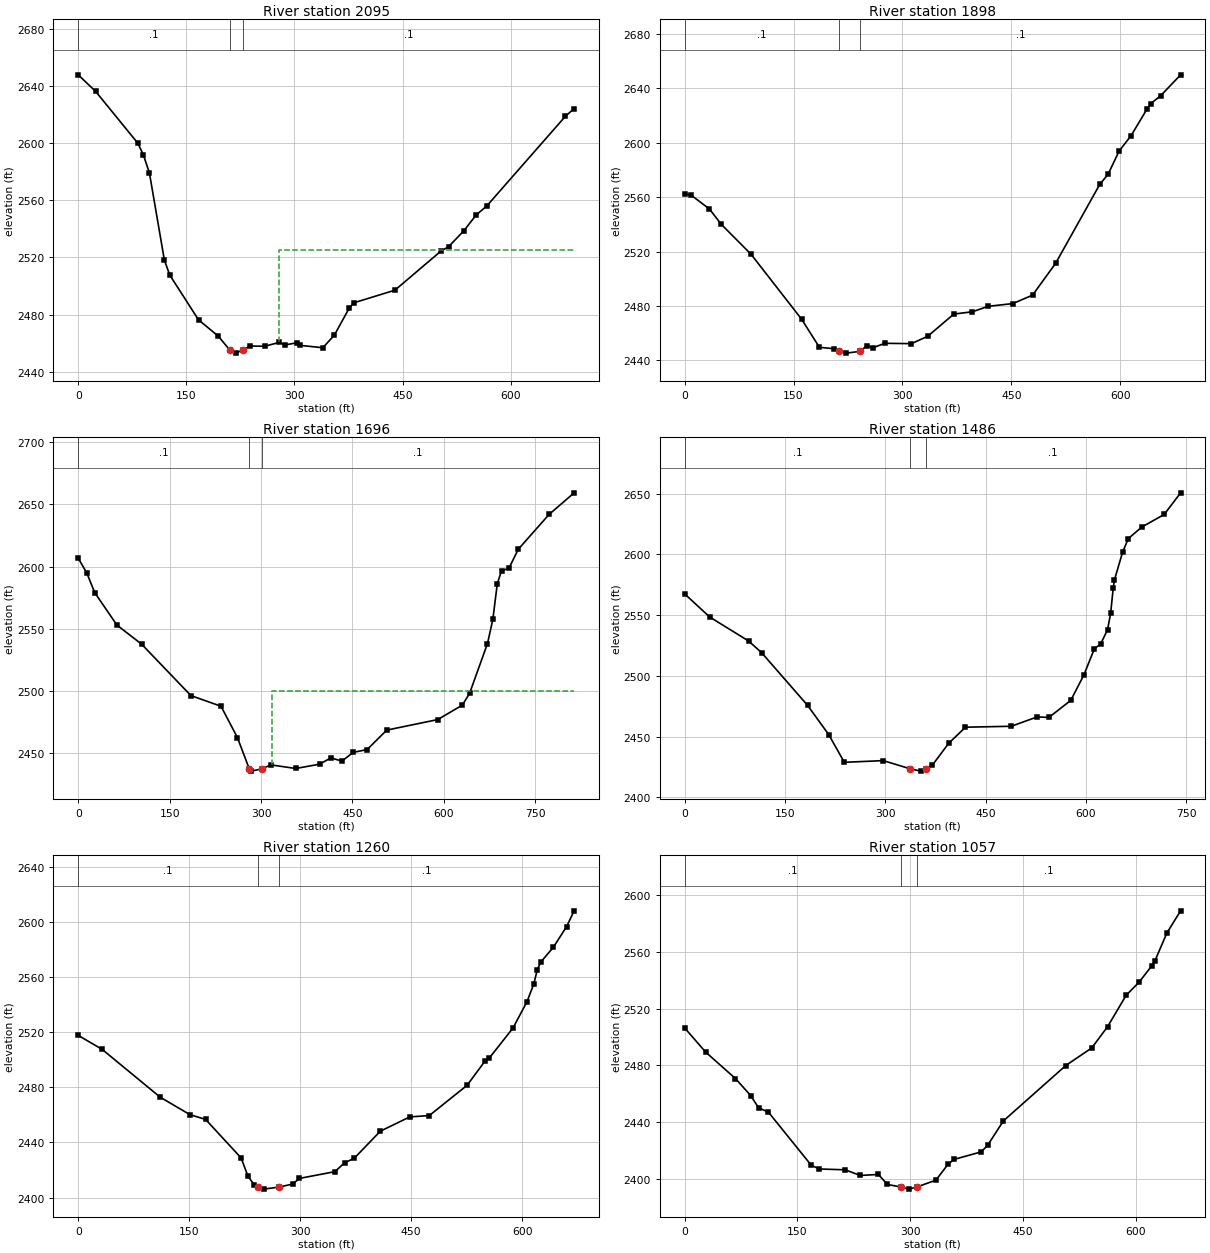
Type RM Length L Ch R = 1 ,2095    ,196.8,197.6,198.3
XS GIS Cut Line= 4
2211428.93687655550711.5466393782211613.54835428550660.949419558
2211796.56510814550636.0355011312212070.69749741550487.382398642
#Sta/Elev= 30
       0 2648.12    24.1 2636.53    82.7 2600.16    90.5 2591.83    98.8 2579.23
   119.5 2518.27   126.9 2507.78   166.9 2476.27   194.1 2464.95   210.2 2455.15
   218.3 2452.93  228.332455.108   238.5 2457.91   258.7 2457.74   278.8 2460.44
   286.9 2458.68   303.1 2460.16   308.3 2458.34   339.4 2456.71   355.5 2465.67
   375.7 2484.26   382.1 2488.18   439.4 2497.09   503.1 2524.46   513.7 2527.54
   534.9 2538.68     552 2549.78   566.8 2556.15   675.9 2619.05     688 2624.47
#Mann= 3 ,-1,0
       0      .1       0   210.2    .045       0  228.33      .1       0
#XS Ineff= 2 , 0
                           278.5            2525
Permanent Ineff=
       F       F
Bank Sta=210.2,228.33
XS Rating Curve= 0 ,0
Exp/Cntr(USF)=0,0
Exp/Cntr=0.3,0.1

Type RM Length L Ch R = 1 ,1898    ,206.2,201.8,188.1
XS GIS Cut Line= 3
2211502.83759858550882.4825539832211856.92915732550805.109951402
2212140.50409147550654.959282854
#Sta/Elev= 30
       0 2562.44     8.9 2561.44    34.1 2551.26    50.5 2539.95    91.4 2518.01
     161  2470.3   185.6 2449.59   206.1  2448.5   212.2 2446.64   222.5 2445.29
  241.912446.595   250.9 2450.86   259.3 2449.21   275.7 2452.51   312.5 2452.27
   334.9  2457.7   370.8    2474   396.5 2475.71   418.1 2479.71   452.1 2481.71
   479.3 2487.93     511 2511.25   571.9 2569.35   583.4 2576.87   598.6 2593.88
   615.1 2605.22     637 2624.77   642.2 2628.77   655.8 2634.54   683.3 2649.91
#Mann= 3 ,-1,0
       0      .1       0   212.2    .045       0  241.91      .1       0
Bank Sta=212.2,241.91
XS Rating Curve= 0 ,0
Exp/Cntr(USF)=0,0
Exp/Cntr=0.3,0.1

Type RM Length L Ch R = 1 ,1696    ,207.4,209.3,206.2
XS GIS Cut Line= 3
2211620.17495273551269.704133954 2211792.4789986550933.300996771
2212172.02947566 550719.24232001
#Sta/Elev= 30
       0 2606.71    14.1 2594.83    27.1 2579.03    63.5 2552.98     104 2537.63
   184.9  2496.3   234.3 2487.73   261.3 2462.47  280.652437.415   283.7  2435.6
   301.7 2437.45   315.9 2440.64     357 2437.72     396 2441.16   414.4 2446.21
   432.7 2443.69   451.2 2450.67   474.1 2452.94   506.2 2468.56   589.9 2477.02
   630.2 2488.63   642.1 2498.05   671.5 2538.13   680.3 2557.53   687.6 2586.23
   694.5 2596.56   706.7 2598.65     722 2613.87   772.6  2641.9   813.7 2659.24
#Mann= 3 ,-1,0
       0      .1       0  280.65    .045       0   301.7      .1       0
#XS Ineff= 2 , 0
                           318.4            2500
Permanent Ineff=
       F       F
Bank Sta=280.65,301.7
XS Rating Curve= 0 ,0
Exp/Cntr(USF)=0,0
Exp/Cntr=0.3,0.1

Type RM Length L Ch R = 1 ,1486    ,224.9,226.5,223.4
XS GIS Cut Line= 4
2211775.26754701551343.9101613812211907.45848168 551152.46122152
2211969.07961267551003.397567748 2212217.5475023550759.992185104
#Sta/Elev= 30
       0 2567.53    37.3 2548.55    95.7  2528.7   115.1 2519.12   183.8 2475.78
   215.4 2451.72   238.8 2428.87     297 2430.28  337.22 2423.54   353.1 2421.62
  360.572423.498   370.5 2426.57   394.9 2444.53     420 2457.79   488.6 2458.55
   527.1 2466.24   544.8 2465.84   577.5 2479.85   597.2 2500.91   612.7 2522.21
   622.3 2526.48   632.5    2538   637.2 2551.87     641 2572.48   642.9  2579.2
   655.1 2602.03   663.6 2613.09   683.9 2622.62   717.2 2632.89   741.8 2650.73
#Mann= 3 ,-1,0
       0      .1       0  337.22    .045       0  360.57      .1       0
Bank Sta=337.22,360.57
XS Rating Curve= 0 ,0
Exp/Cntr(USF)=0,0
Exp/Cntr=0.3,0.1

Type RM Length L Ch R = 1 ,1260    ,205.8,202.5,196.9
XS GIS Cut Line= 3
2212011.42551952551430.8391782042212163.36912259551084.745415669
2212287.20778492550819.830781417
#Sta/Elev= 30
       0 2517.67    32.4 2507.48     111 2472.76   151.1 2460.15   172.2  2456.7
   220.2 2428.79   229.5 2415.49   237.7 2409.42   243.2 2407.64   250.8 2406.16
  271.94 2407.68   290.1 2409.89   298.9 2413.92   346.9 2418.82     360 2425.22
   373.1 2428.52   408.3 2448.14   448.1 2458.52   474.6 2459.51   525.7 2481.46
   549.7 2498.89   555.8 2501.26   587.7 2522.97   606.6 2542.01     616 2555.16
   620.4 2564.97     625 2570.63   642.4 2581.63   660.1 2596.47   670.4 2607.97
#Mann= 3 ,-1,0
       0      .1       0   243.2    .045       0  271.94      .1       0
Bank Sta=243.2,271.94
XS Rating Curve= 0 ,0
Exp/Cntr(USF)=0,0
Exp/Cntr=0.3,0.1

Type RM Length L Ch R = 1 ,1057    ,200,199.9,199.7
XS GIS Cut Line= 4
2212225.36818851551506.7373152262212297.98203641551345.509958015
2212321.36615692551131.3606438572212402.59520712550876.596804599
#Sta/Elev= 30
       0 2506.32      28 2489.33    67.5 2470.75      88 2458.65    98.2 2450.19
   111.4 2447.09   168.4  2409.7   179.1 2407.11   213.4 2406.52   233.5 2402.56
   257.6 2403.25   269.7 2396.19   287.6 2394.46   297.9 2392.93  308.862394.452
   334.1 2399.22   350.2 2410.41   358.2 2413.84   394.5 2419.16   402.9 2423.75
   423.9 2440.94   506.8  2479.9   541.5 2492.33   562.5 2507.28   587.2  2529.4
   604.5 2538.64   621.3 2550.16   625.3 2553.43   641.3 2573.18   659.6 2588.79
#Mann= 3 ,-1,0
       0      .1       0   287.6    .045       0  308.86      .1       0
Bank Sta=287.6,308.86
XS Rating Curve= 0 ,0
Exp/Cntr(USF)=0,0
Exp/Cntr=0.3,0.1