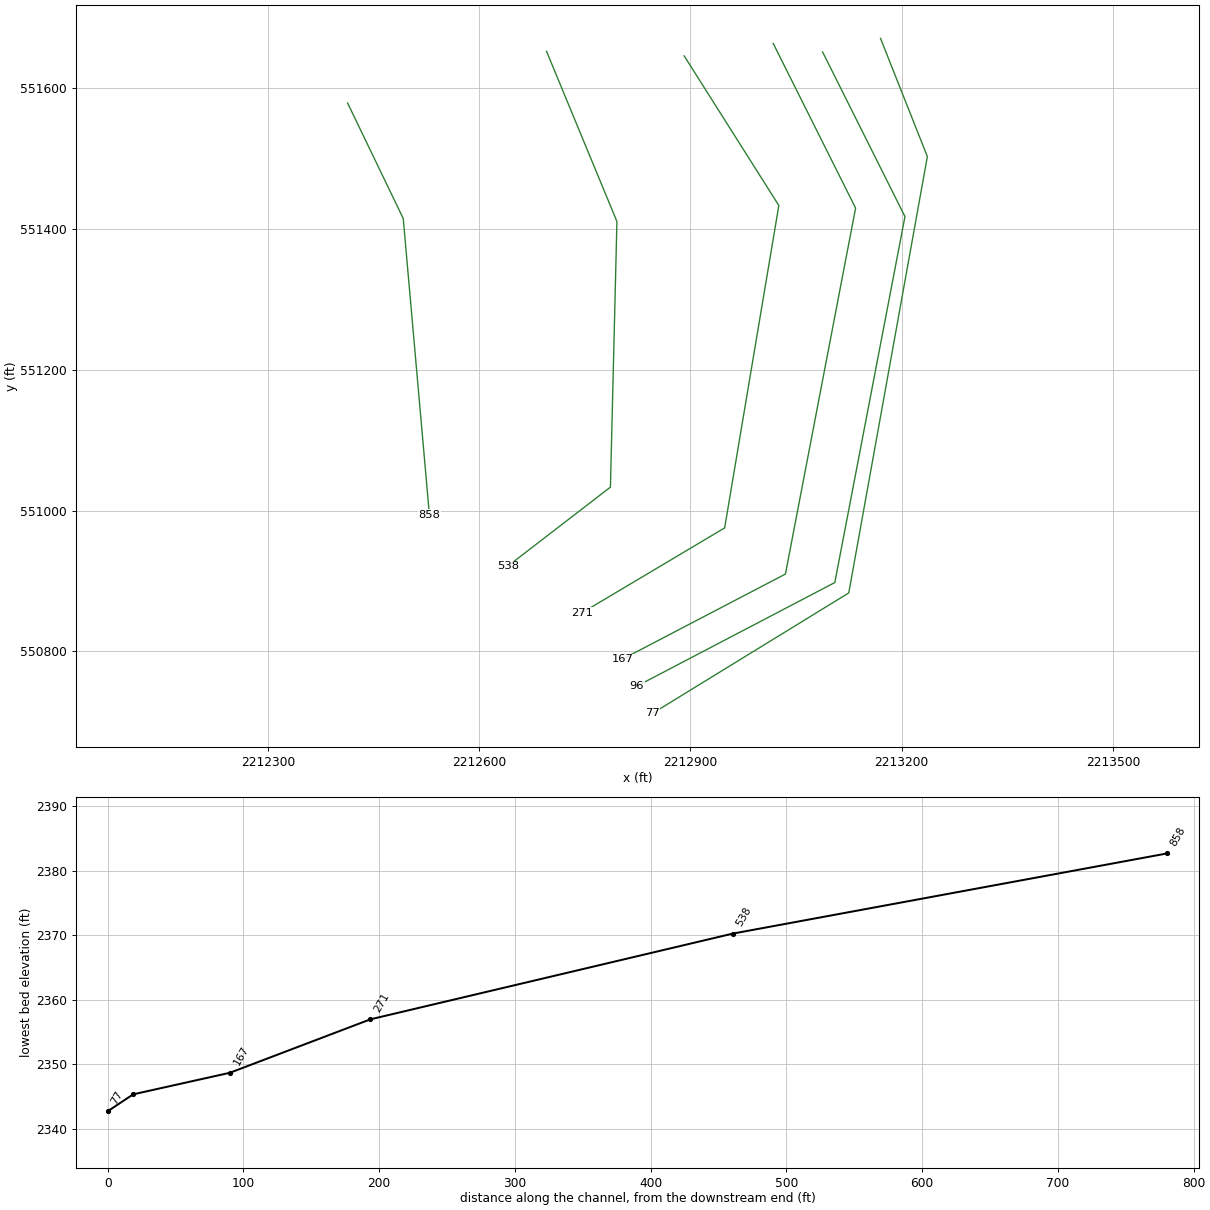
HEC-RAS study CHIMRCKRN.prj: CHIMRCKRN

--- CHIMRCKRN.g01 (geometry) --- (continued)

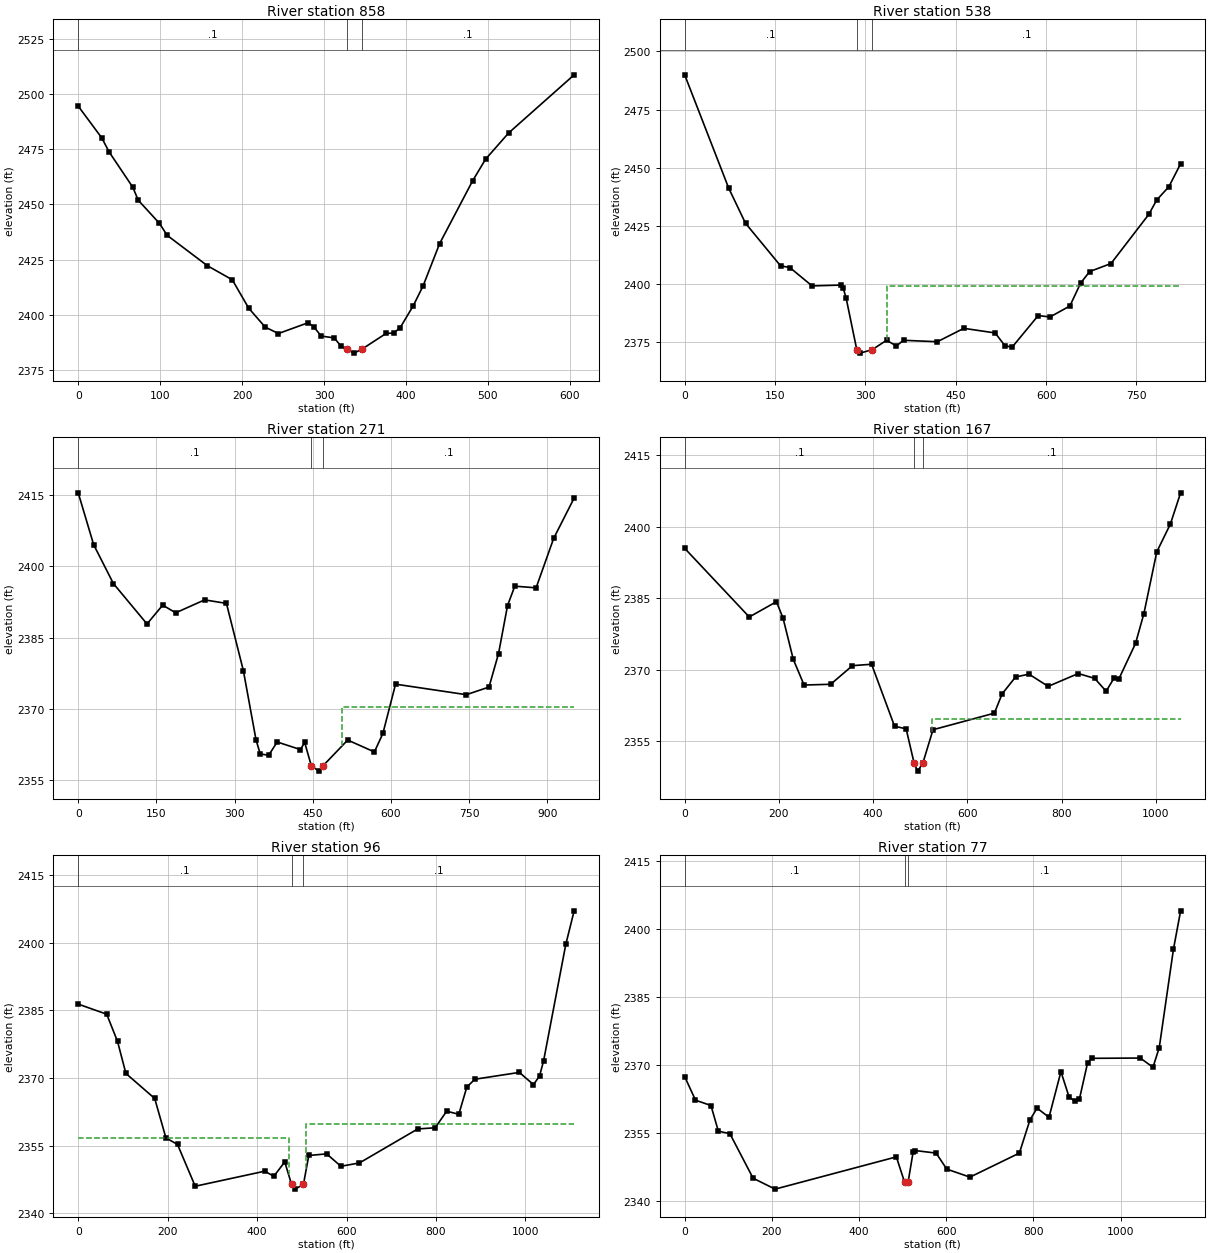
Type RM Length L Ch R = 1 ,858     ,319.9,319.9,314.9
XS GIS Cut Line= 3
2212413.18692682551579.1629948392212492.19760041 551415.06390353
 2212529.3920237550993.595663393
#Sta/Elev= 30
       0 2494.41    28.8 2480.01    37.7 2473.69    66.7 2457.66    73.2 2451.87
    99.1 2441.38   108.6 2435.93   157.6 2422.21     188 2415.85   208.1 2402.97
   228.1 2394.46   244.3 2391.52   280.4 2396.39   287.2 2394.69   296.5 2390.38
   312.5 2389.55   320.6 2385.82   327.8 2384.33   336.6 2382.66   346.2 2384.45
   375.7 2391.57   384.8 2391.74   392.8 2394.11   408.9 2404.12   420.9 2413.12
     441 2432.18   481.2 2460.56   497.2 2470.45   525.3 2482.28   605.2 2508.57
#Mann= 3 ,-1,0
       0      .1       0   327.8    .045       0   346.2      .1       0
Bank Sta=327.8,346.2
XS Rating Curve= 0 ,0
Exp/Cntr(USF)=0,0
Exp/Cntr=0.3,0.1

Type RM Length L Ch R = 1 ,538     ,261.6,267.1,256.1
XS GIS Cut Line= 4
 2212695.6945571551652.6494549472212795.65313081551410.795400935
 2212786.4255958551033.2980526962212640.66582899550920.945884973
#Sta/Elev= 30
       0 2489.91      73 2441.23     101 2426.07   159.2 2407.77   174.5 2407.05
   211.5 2399.15   259.1  2399.5   263.3 2398.06     268 2393.95  285.712371.721
   291.3 2370.24   311.3 2371.73   335.3 2375.79   351.3 2373.31   363.3 2375.76
   419.4 2375.14   463.4  2380.9   515.4 2378.92   531.4 2373.51   543.4 2372.74
   586.9  2386.4   606.5 2385.79   639.5 2390.52   657.3 2400.36   672.3 2405.31
   707.8 2408.78   770.5 2429.91   783.6 2436.08   803.8  2441.8   823.3 2451.66
#Mann= 3 ,-1,0
       0      .1       0  285.71    .045       0   311.3      .1       0
#XS Ineff= 2 , 0
                           335.3            2399
Permanent Ineff=
       F       F
Bank Sta=285.71,311.3
XS Rating Curve= 0 ,0
Exp/Cntr(USF)=0,0
Exp/Cntr=0.3,0.1

Type RM Length L Ch R = 1 ,271     ,104.5,103.5,103.6
BEGIN DESCRIPTION:
structure xs 4
END DESCRIPTION:
XS GIS Cut Line= 4
2212891.13601763551646.1955004522213025.59209377551433.552285052
2212948.63895604550975.3418533262212746.37862104550854.938247555
#Sta/Elev= 30
       0 2415.42    29.6 2404.53    67.5 2396.36     132 2387.87   162.1 2391.83
     187 2390.21   242.6 2392.93   284.4 2392.19   316.9 2378.07   341.2 2363.52
   349.3 2360.54   365.5  2360.3   381.8 2363.07   426.4 2361.48   434.5 2362.98
   447.22358.103   461.5 2356.95   469.7 2358.07   517.1 2363.48   568.3 2360.98
   584.6 2364.86   608.9 2375.22   744.7 2373.01   788.2 2374.61   806.5 2381.64
   823.8 2391.74   837.7 2395.81   878.6 2395.46   912.3 2405.86   951.6 2414.33
#Mann= 3 ,-1,0
       0      .1       0   447.2    .045       0   469.7      .1       0
#XS Ineff= 2 , 0
                          506.38          2370.5
Permanent Ineff=
       F       F
Bank Sta=447.2,469.7
XS Rating Curve= 0 ,0
Exp/Cntr(USF)=0,0
Exp/Cntr=0.5,0.3

Type RM Length L Ch R = 1 ,167     ,72.1,71.2,71.2
BEGIN DESCRIPTION:
structure xs 3
END DESCRIPTION:
XS GIS Cut Line= 4
2213017.58790292551663.8480220292213134.58447728 551429.85487331
2213034.95571816 550909.755263892212803.30642478550788.704563962
#Sta/Elev= 30
       0 2395.49   137.1 2381.06   194.7 2384.27   208.7 2380.85   230.5 2372.15
   253.4 2366.76   309.8 2366.92     356 2370.83   396.7 2371.13   445.4  2358.1
     470 2357.56     487 2350.31   494.4 2348.67  505.372350.329     527 2357.37
   657.3 2360.85   673.6 2364.89   702.2 2368.45   730.7 2369.05   771.4 2366.48
   835.2 2369.18   870.1 2368.16   894.4 2365.46   911.6 2368.28   921.1 2367.97
   956.8  2375.5   974.5 2381.75  1001.9 2394.74  1030.8  2400.6  1052.5 2407.15
#Mann= 3 ,-1,0
       0      .1       0     487    .045       0  505.37      .1       0
#XS Ineff= 2 , 0
             467  2356.7  525.37          2359.7
Permanent Ineff=
       F       F
Bank Sta=487,505.37
XS Rating Curve= 0 ,0
Exp/Cntr(USF)=0,0
Exp/Cntr=0.5,0.3

Type RM Length L Ch R = 1 ,96      ,27.3,18.8,18.9
BEGIN DESCRIPTION:
structure xs 2
END DESCRIPTION:
XS GIS Cut Line= 5
2213087.69700608 551651.768738182213204.69358044551417.775589461
2213188.42989387551332.7811424972213105.06482132550897.675980041
2212823.71692927550750.356020817
#Sta/Elev= 30
       0 2386.37    63.7 2384.13    87.9 2378.09   106.6 2370.99     171 2365.44
   196.1 2356.69     222 2355.24   261.6 2345.97     417 2349.31   437.3 2348.18
   461.8 2351.37  476.862346.415   484.7 2345.33   503.5 2346.36   515.5 2352.79
   555.5 2353.15   587.3  2350.4   628.8 2351.14   759.1 2358.68   798.1 2358.94
   823.8 2362.62   850.9 2361.93   868.9 2367.99     887 2369.71   986.3 2371.22
  1017.9 2368.51  1031.5 2370.44  1040.5  2373.8  1090.2 2399.66  1108.8 2407.06
#Mann= 3 ,-1,0
       0      .1       0  476.86    .045       0   503.5      .1       0
#XS Ineff= 2 , 0
          470.56  2356.7   509.8          2359.7
Permanent Ineff=
       F       F
Bank Sta=476.86,503.5
XS Rating Curve= 0 ,0
Exp/Cntr(USF)=0,0
Exp/Cntr=0.5,0.3

Type RM Length L Ch R = 1 ,77      ,,,
BEGIN DESCRIPTION:
structure xs 1
END DESCRIPTION:
XS GIS Cut Line= 4
2213169.95945287551671.109514983 2213236.4949667551503.072673616
2213124.87694533 550882.914061372212846.18353716550711.751573407
#Sta/Elev= 30
       0 2367.48    24.8 2362.29    60.3 2361.11    77.2 2355.48   103.8  2354.9
     157 2345.11   207.5 2342.71   485.7 2349.81  504.492344.251  512.662344.263
   524.1 2350.86   528.1 2351.21   576.9 2350.64   601.3 2347.12   654.5 2345.35
   767.9 2350.64   792.3 2357.97   808.6 2360.53   835.9 2358.52   863.3 2368.56
   882.1 2362.95   896.2 2362.05   905.6 2362.48   924.3 2370.44   933.7  2371.5
  1045.3 2371.56  1074.5 2369.53  1088.9 2373.87  1121.5 2395.54  1137.9 2403.96
#Mann= 3 ,-1,0
       0      .1       0  504.49    .045       0  512.66      .1       0
Bank Sta=504.49,512.66
XS Rating Curve= 0 ,0
Exp/Cntr(USF)=0,0
Exp/Cntr=0.3,0.1
LCMann Table=0

Chan Stop Cuts=-1
Use User Specified Reach Order=0
Composite Channel Slope=5